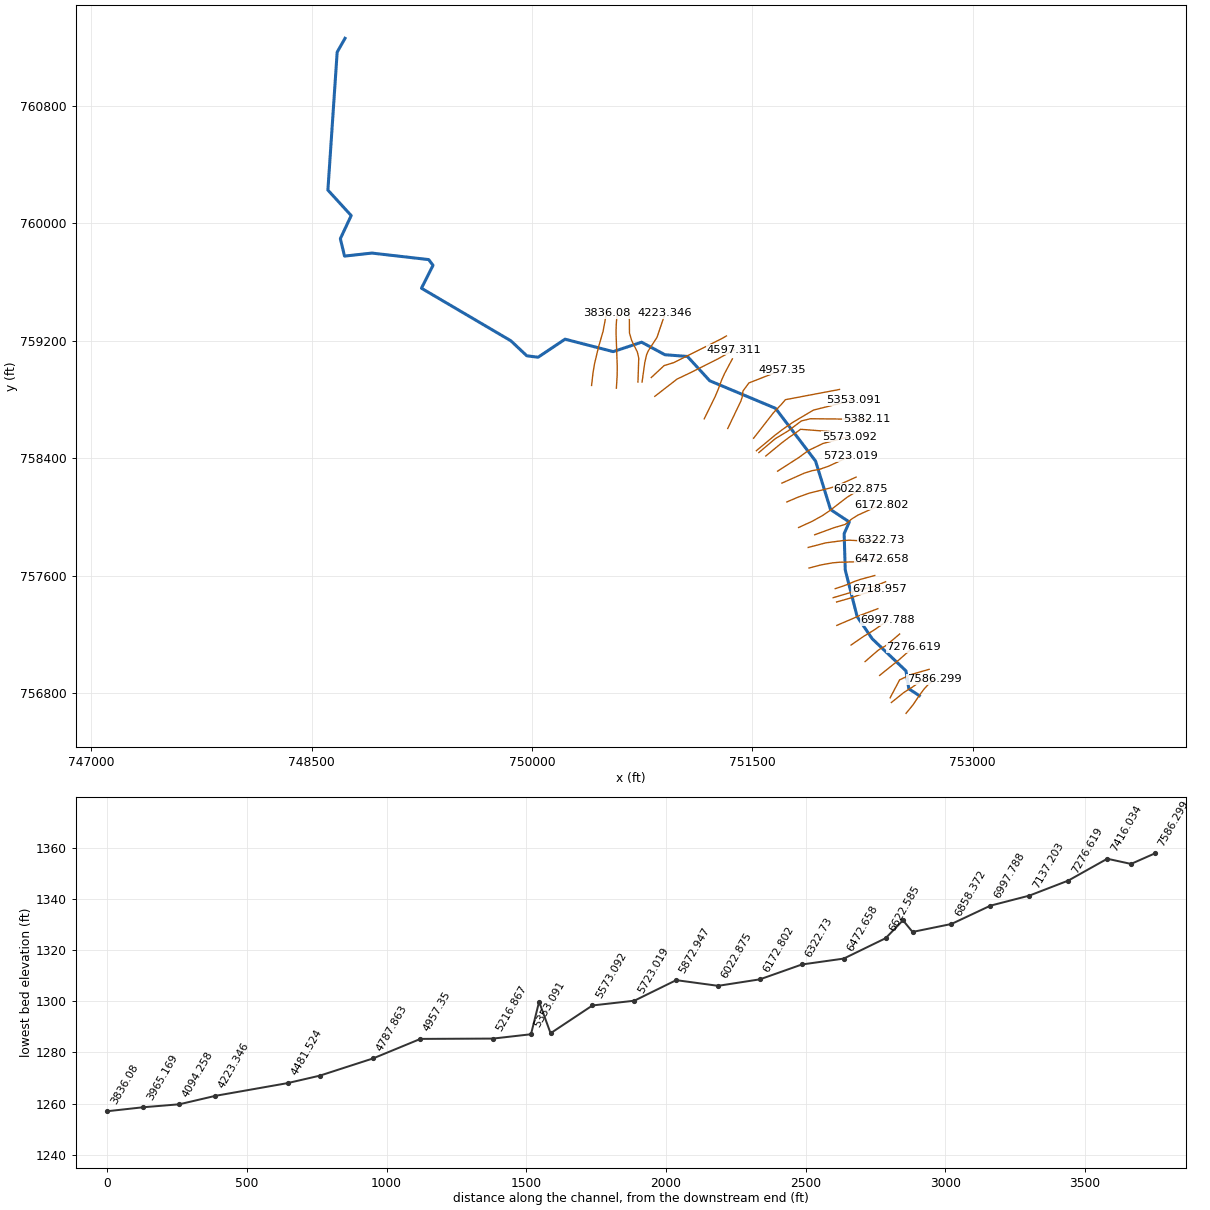
--- 14322_ras.prj (project) ---

Proj Title=14322
Current Plan=p01
Default Exp/Contr=0.3,0.1
English Units
Geom File=g01
Flow File=f01
Plan File=p01
Y Axis Title=Elevation
X Axis Title(PF)=Main Channel Distance
X Axis Title(XS)=Station
BEGIN DESCRIPTION:
RFD model 14322 exported to HEC-RAS
END DESCRIPTION:

--- 14322_ras.p01 (plan) ---

Plan Title=Plan 01
Program Version=4.10
Short Identifier=Plan 01
Geom File=g01
Flow File=f01
Subcritical Flow
Calc Critical at every XS
Secant Critical Depth

--- 14322_ras.f01 (steady flow) ---

Flow Title=Flow 01
Program Version=5.01
Number of Profiles= 6
Profile Names=10yr,25yr,50yr,100yr,100plus,500yr
River Rch & RM=14322,45,7586.299
  221.57  374.33  523.72  669.08  976.85 1726.69
River Rch & RM=14322,45,7276.619
  225.38  381.11  533.52  681.95  995.64 1757.17
River Rch & RM=14322,45,7137.203
  273.09  464.43  652.72  837.05  1222.1 2110.31
River Rch & RM=14322,45,6718.957
  278.43  473.92  666.43  855.07  1248.4 2151.61
River Rch & RM=14322,45,6622.585
  280.35  477.34  671.39  861.59 1257.92 2166.55
River Rch & RM=14322,45, 6322.73
  288.18  491.31  691.65  888.26 1296.86 2227.77
River Rch & RM=14322,45,6022.875
  292.85  499.67   703.8  904.29 1320.26 2264.55
River Rch & RM=14322,45,5872.947
  295.62  504.64  711.03  913.84 1334.21  2286.5
River Rch & RM=14322,45,5723.019
  297.23  507.54  715.24   919.4 1342.33 2299.27
River Rch & RM=14322,45,5573.092
  298.61  510.02  718.85  924.17 1349.28  2310.2
River Rch & RM=14322,45,5423.164
  301.14  514.56  725.45  932.88 1362.01 2330.17
River Rch & RM=14322,45,5353.091
  302.29  516.62  728.45  936.84 1367.79 2339.22
River Rch & RM=14322,45, 4957.35
  338.67  581.91  823.48 1062.38 1551.07 2623.97
River Rch & RM=14322,45,4787.863
   342.7  589.13  833.98 1076.24 1571.31 2655.04
River Rch & RM=14322,45,4597.311
  347.39  597.53   846.2 1092.37 1594.86  2691.1
River Rch & RM=14322,45,4481.524
  358.89  618.15  876.21 1132.01 1652.73 2779.61
River Rch & RM=14322,45,4223.346
  359.99  620.13  879.09 1135.81 1658.28 2788.06
River Rch & RM=14322,45,4094.258
  363.75  626.86  888.87 1148.72 1677.14 2816.72
River Rch & RM=14322,45,3965.169
  385.35  665.59  945.25 1223.19 1785.86 2981.42
River Rch & RM=14322,45, 3836.08
  398.64  689.36  979.79 1268.76 1852.39 3081.14
River Rch & RM=14322,45,3577.902
  415.99  720.47 1025.07 1328.56  1939.7 3211.63
River Rch & RM=14322,45,3504.383
  418.78  725.46 1032.32 1338.13 1953.67 3232.38
River Rch & RM=14322,45,3321.559
  421.14  729.68 1038.46 1346.23 1965.49  3249.9
River Rch & RM=14322,45,3180.143
  423.93  734.66  1045.7 1355.78 1979.43 3270.55
River Rch & RM=14322,45,3038.728
  427.54  741.14 1055.12 1368.21 1997.59 3297.48
River Rch & RM=14322,45,2897.312
   430.1  745.72 1061.78    1377 2010.42 3316.43
River Rch & RM=14322,45,2755.897
  438.34  760.49 1083.27 1405.39 2051.86 3377.75
River Rch & RM=14322,45,2614.481
  439.61  762.76 1086.57 1409.75 2058.23 3387.15
River Rch & RM=14322,45,2473.066
  440.45  764.27 1088.77 1412.65 2062.47 3393.41
Boundary for River Rch & Prof#=14322,45,1
Up Type= 0
Dn Type= 2
Boundary for River Rch & Prof#=14322,45,2
Up Type= 0
Dn Type= 2
Boundary for River Rch & Prof#=14322,45,2
Up Type= 0
Dn Type= 2
Boundary for River Rch & Prof#=14322,45,2
Up Type= 0
Dn Type= 2
Boundary for River Rch & Prof#=14322,45,2
Up Type= 0
Dn Type= 2
Boundary for River Rch & Prof#=14322,45,2
Up Type= 0
Dn Type= 2

--- 14322_ras.g01 (geometry) ---

Geom Title=14322
Program Version=4.10

River Reach=14322,45
Reach XY= 30
752637.435041338756785.160818964752565.907263547756832.035818964
752546.532263577756953.771930069752316.671152413757172.521930069
 752214.24059692757323.285818949752133.129485786 757641.06359674
752125.629485726757887.535818949 752160.95904991757967.291474581
752032.972938806758052.360919043751931.236827642758381.874807939
751658.320161015758741.249807939751210.750716597758928.749807909
751058.667383283759094.374807909750905.472938806  759105.9025857
750747.139605492759191.319252357750553.736827701759127.083141282
 750225.95904991759211.805363491750042.278494358 759088.88869682
749965.542383224759098.610919043 749857.20904991759200.694252357
749248.487541497 759558.61733067749327.219612002759714.581036612
749297.636278689759753.539369971748910.969612002759797.914369971
748724.719611973759777.289369985748696.327435941759895.980825767
748770.205723137760053.192147762748611.594612002760226.664369956
748674.650167584761165.723397747748727.932959467761259.645245954

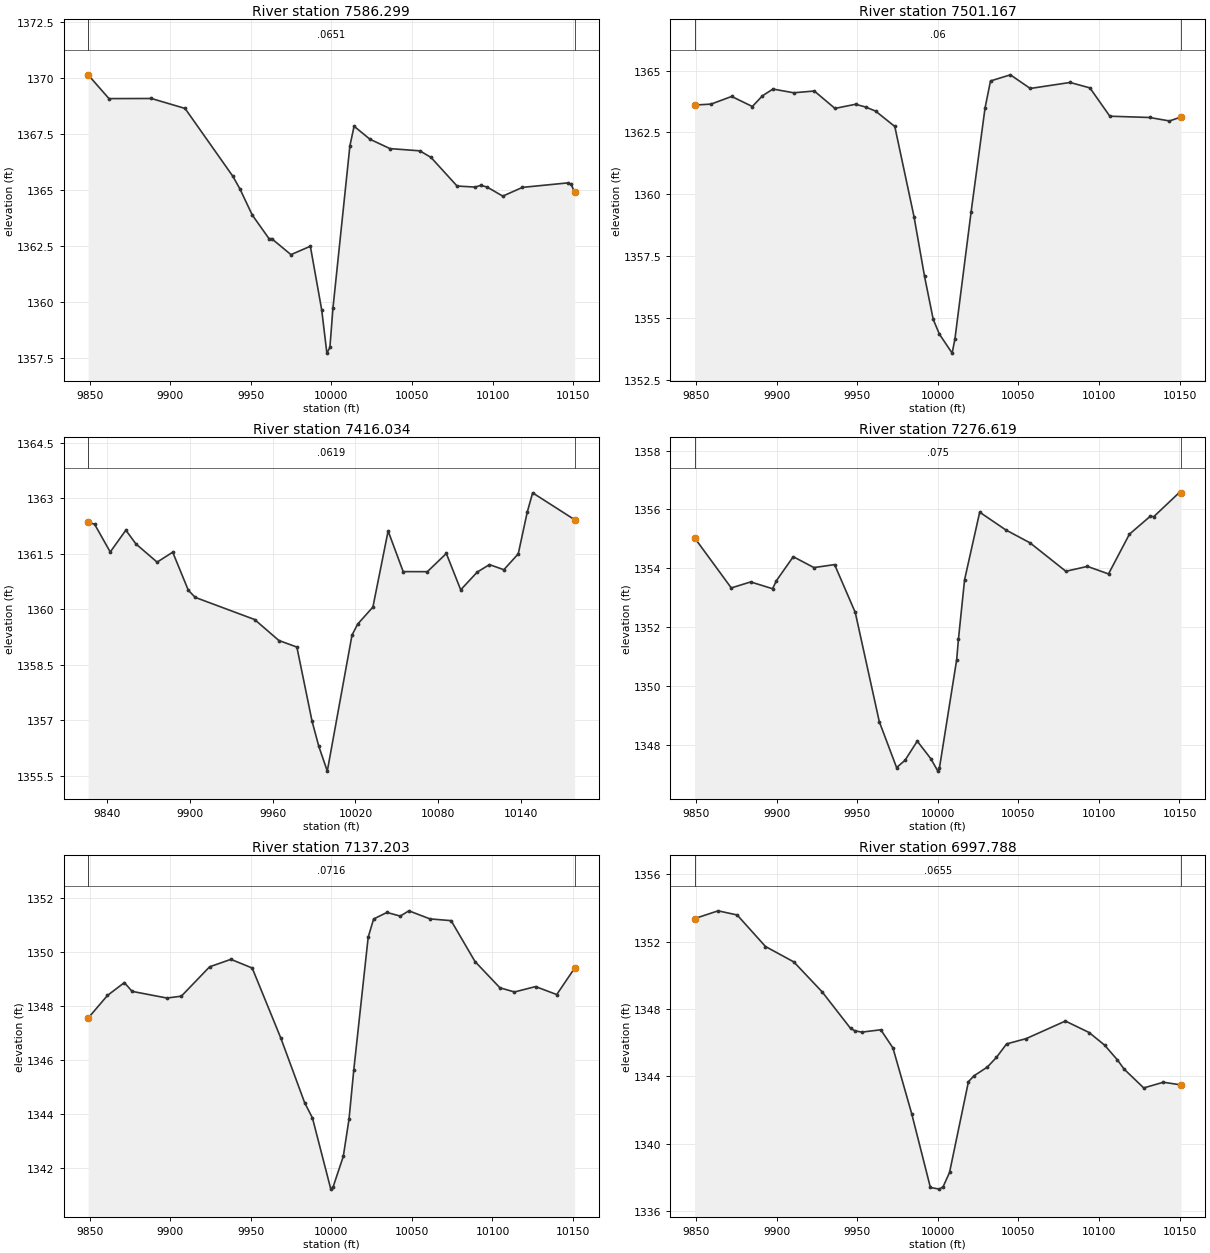
Type RM Length L Ch R = 1 ,7586.299,85.132200,85.132200,85.132200
XS GIS Cut Line= 6
752546.765590272756664.680112998752593.355348273756721.264198713
752633.154362327756780.880215715752669.262881009756829.926049498
752697.632923228 756860.34880963752738.309053496756896.514014489
#Sta/Elev= 30
9849.045 1370.14    98621369.078 9888.321369.0839909.1971368.6399938.857 1365.61
9943.3141365.0359950.8811363.8829961.3251362.8219962.9041362.8269974.9281362.109
9986.9511362.4849994.0221359.6319997.207 1357.719999.0761357.962   100011359.732
 10011.5 1366.97 10014.11367.84310023.931367.26410036.371366.84510054.931366.745
10061.861366.449   100781365.17310089.211365.12710092.661365.20310096.521365.132
10106.381364.72310118.571365.11310146.531365.31210148.671365.26210150.951364.896
#Mann= 3 , 0 , 0
9849.045  0.0651       09849.045  0.0651       010150.95  0.0651       0
#XS Ineff= 2 , 0
       0                               0
Bank Sta=9849.045,10150.95
Exp/Cntr=0.3,0.1

Type RM Length L Ch R = 1 ,7501.167,85.132300,85.132300,85.132300
XS GIS Cut Line= 6
752447.032118351756738.646732531752530.479250435756805.536635049
752566.561084047756828.937341157752568.287459252756829.947107789
752589.697326695756843.148540466752690.836449063756916.313535514
#Sta/Elev= 30
9849.0471363.6079859.2591363.6459872.0751363.9549884.8911363.5489891.1821363.981
9897.7071364.2529910.5241364.102 9923.341364.1739936.1561363.4729948.9721363.638
9955.1361363.5289961.3831363.3639973.3011362.743 9985.221359.1099991.7641356.696
9997.1391354.963   100011354.36410008.89  1353.610010.631354.17510020.631359.279
10029.311363.487 10032.71364.57910045.041364.82610057.381364.27610082.071364.518
10094.411364.29810106.751363.15710131.441363.10510143.781362.96510150.981363.126
#Mann= 3 , 0 , 0
9849.047    0.06       09849.047    0.06       010150.98    0.06       0
#XS Ineff= 2 , 0
       0                               0
Bank Sta=9849.047,10150.98
Exp/Cntr=0.3,0.1

Type RM Length L Ch R = 1 ,7416.034,139.415500,139.415500,139.415500
XS GIS Cut Line= 4
752438.897419006756770.840878025752503.181670219756892.970814869
752583.161575019756929.628271207752704.188551426756964.484040439
#Sta/Elev= 30
 9826.591362.349 9831.291362.297 9842.591361.5479853.8911362.1379861.1611361.766
9876.4921361.2739887.7931361.5429899.0941360.511  9904.1 1360.329947.0391359.722
9964.6051359.1559977.6051358.9789988.6061356.9719993.4761356.2959999.6061355.625
10017.48  1359.310021.611359.59910032.611360.05910043.611362.115 10054.51361.017
   100721361.01510085.721361.50710096.121360.52510108.131361.00610116.941361.206
10127.341361.06810137.751361.49710144.261362.62510148.161363.14610178.53 1362.42
#Mann= 3 , 0 , 0
 9826.59  0.0619       0 9826.59  0.0619       010178.53  0.0619       0
#XS Ineff= 2 , 0
       0                               0
Bank Sta=9826.59,10178.53
Exp/Cntr=0.3,0.1

Type RM Length L Ch R = 1 ,7276.619,139.415600,139.415600,139.415600
XS GIS Cut Line= 6
752367.246267813756923.210060217752484.176045958757017.120562429
752485.770230255757018.328277803752497.988893528757028.045082123
752557.714496383757081.069347903752599.703534511757115.832419159
#Sta/Elev= 30
9849.0271355.0359871.7981353.3319883.8251353.535 9897.451353.3049899.7951353.576
9910.2761354.3939923.1021354.0239935.9271354.1249948.7531352.4989963.6741348.783
9974.4051347.2229979.644 1347.479987.2311348.1219995.6141347.52710000.031347.101
   100011347.20510011.721350.89510012.791351.58410016.61 1353.6110025.991355.907
10042.151355.30510057.211354.86510079.481353.89710092.851354.06310105.941353.807
10118.921355.159 10131.9 1355.77   101341355.75310149.681356.56510150.991356.553
#Mann= 3 , 0 , 0
9849.027   0.075       09849.027   0.075       010150.99   0.075       0
#XS Ineff= 2 , 0
       0                               0
Bank Sta=9849.027,10150.99
Exp/Cntr=0.3,0.1

Type RM Length L Ch R = 1 ,7137.203,139.415500,139.415500,139.415500
XS GIS Cut Line= 6
 752267.99198247 757017.13095414752353.554308314757091.172531176
752370.727586988757103.614307672752397.611987016757118.064874661
752414.607375738 757129.65298995752503.468909028757204.976965672
#Sta/Elev= 30
9849.0271347.5559861.0531348.3959871.5191348.8699876.3351348.5459897.9681348.298
9906.8991348.3689924.4161349.4539937.641 1349.739950.8651349.4099968.7011346.805
9983.384 1344.439988.2571343.8619999.6461341.228   100011341.29610007.391342.437
10010.951343.81610013.911345.63910022.851350.55110026.221351.22310034.481351.465
10042.75 1351.33 10048.11351.52510061.211351.22610074.321351.16210089.14 1349.65
10104.611348.67710113.651348.52310126.761348.72210139.871348.42710150.971349.406
#Mann= 3 , 0 , 0
9849.027  0.0716       09849.027  0.0716       010150.97  0.0716       0
#XS Ineff= 2 , 0
       0                               0
Bank Sta=9849.027,10150.97
Exp/Cntr=0.3,0.1

Type RM Length L Ch R = 1 ,6997.788,139.415600,139.415600,139.415600
XS GIS Cut Line= 6
752172.987941052757129.976132561752258.488270465757189.068455955
752298.118124844757212.515179969752299.654567403757213.795548768
752329.784265808757232.252349807752424.063684574757297.491938777
#Sta/Elev= 30
 9849.02 1353.379863.6221353.8329875.4441353.5869893.0331351.7129910.6211350.797
9928.2091349.0169945.7981346.8519948.7131346.6969952.9541346.6279964.6021346.765
9972.1391345.6859983.7581341.7889995.3771337.396   100011337.29810003.311337.447
10007.271338.291   100191343.68410022.45 1344.0310030.72 1344.5510036.331345.119
10042.681345.92510054.84 1346.2410079.161347.28410093.881346.60310103.481345.856
10111.461344.97510115.641344.425 10127.8 1343.3110139.961343.64910150.981343.489
#Mann= 3 , 0 , 0
 9849.02  0.0655       0 9849.02  0.0655       010150.98  0.0655       0
#XS Ineff= 2 , 0
       0                               0
Bank Sta=9849.02,10150.98
Exp/Cntr=0.3,0.1

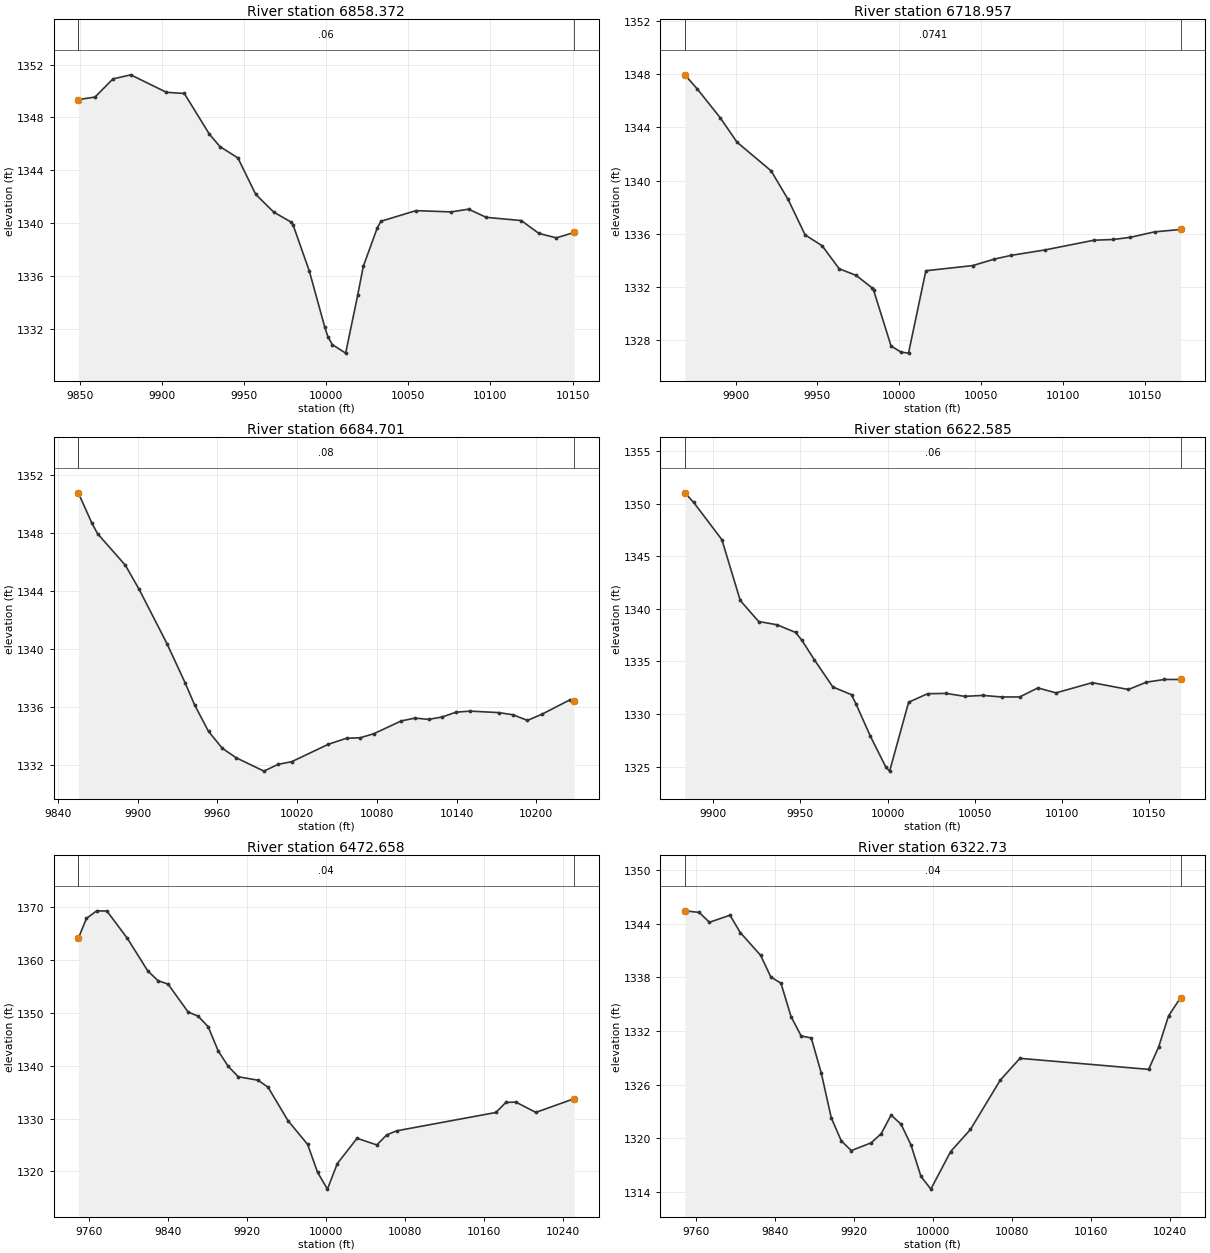
Type RM Length L Ch R = 1 ,6858.372,139.415500,139.415500,139.415500
XS GIS Cut Line= 5
752075.650148061757263.614386166 752213.56765166757322.544550647
752214.981865225757323.958764206752231.765357308757330.798786078
752355.132050103757377.355563135
#Sta/Elev= 30
 9849.021349.3519859.1881349.5439870.0621350.9159880.9371351.2279902.6861349.903
9913.5611349.8169928.8981346.722 9935.311345.7899946.1851344.9359957.0591342.174
9967.9341340.8379978.8081340.0589979.7991339.8619989.6831336.369    99991332.162
10001.021331.38410003.761330.78810011.821330.14910019.121334.51810022.581336.729
10031.021339.61310033.271340.13510054.651340.94210076.021340.84510086.711341.052
 10097.41340.43410118.78 1340.1910129.471339.21710140.151338.87910150.98 1339.29
#Mann= 3 , 0 , 0
 9849.02    0.06       0 9849.02    0.06       010150.98    0.06       0
#XS Ineff= 2 , 0
       0                               0
Bank Sta=9849.02,10150.98
Exp/Cntr=0.3,0.1

Type RM Length L Ch R = 1 ,6718.957,34.255500,34.255500,34.255500
XS GIS Cut Line= 6
752074.266601503 757422.89547919752172.785737345757450.911092492
752198.801991004757460.320994948752200.644490126757461.098939024
 752232.21655857757472.217741544752364.549993799757509.302900402
#Sta/Elev= 25
9868.9091347.9459876.6031346.8749890.4651344.7349900.8611342.8799921.6541340.731
 9932.051338.5789942.4471335.9179952.8431335.101 9963.241333.3749973.6891332.871
9983.3561331.9359984.3231331.7499994.9571327.573   100011327.10910005.621327.033
10016.221333.22410044.781333.60910058.131334.10110068.521334.38410089.291334.793
 10118.91335.51710130.831335.57310141.221335.73510155.961336.146 10171.91336.326
#Mann= 3 , 0 , 0
9868.909  0.0741       09868.909  0.0741       0 10171.9  0.0741       0
#XS Ineff= 2 , 0
       0                 10032.4       0
Bank Sta=9868.909,10171.9
Exp/Cntr=0.3,0.1

Type RM Length L Ch R = 1 ,6684.701,62.115800,62.115800,62.115800
XS GIS Cut Line= 4
752051.086011618757452.055063173 752215.00000003757500.913919821
752326.617771566757528.231490895 752407.65652445757560.646992072
#Sta/Elev= 30
9855.2871350.7959865.5961348.6819869.8061347.9689890.6751345.797 9901.111344.119
 9921.981340.3859935.6111337.6889942.8491336.1429953.284 1334.329963.7191333.149
9974.1541332.4969995.0231331.57610005.621332.04310015.891332.22710043.521333.432
10057.211333.84910067.511333.879 10077.81334.16410098.391335.04410108.691335.238
10118.981335.15110129.281335.31710139.571335.64710150.271335.72110171.811335.617
10182.581335.46610193.351335.07810204.121335.49910225.661336.51510228.521336.393
#Mann= 3 , 0 , 0
9855.287    0.08       09855.287    0.08       010228.52    0.08       0
#XS Ineff= 2 , 0
       0                10035.35       0
Bank Sta=9855.287,10228.52
Exp/Cntr=0.3,0.1

Type RM Length L Ch R = 1 ,6622.585,149.927700,149.927700,149.927700
XS GIS Cut Line= 6
752064.836882947757513.420777473752118.009539339757531.087717548
752157.322338306757545.804568693752195.831754637757562.698636417
752235.870514817757576.605320032752333.988057645757603.258373605
#Sta/Elev= 29
9883.8081351.0169888.8161350.1259905.0551346.5689915.5921340.792 9926.131338.795
9936.6671338.4849947.3031337.7589950.9981336.9939957.9811335.1789968.6581332.577
9979.3361331.8449981.8161331.0029990.2161327.882    99991324.97110001.181324.585
10012.071331.12910022.961331.93810033.581331.96610044.161331.68910054.751331.775
10065.331331.62910075.74 1331.6310086.131332.48810096.531332.01810117.311332.987
10138.021332.33810148.341333.03510158.661333.29110167.941333.288
#Mann= 3 , 0 , 0
9883.808    0.06       09883.808    0.06       010167.94    0.06       0
#XS Ineff= 2 , 0
       0                               0
Bank Sta=9883.808,10167.94
Exp/Cntr=0.3,0.1

Type RM Length L Ch R = 1 ,6472.658,149.927600,149.927600,149.927600
XS GIS Cut Line= 6
751887.010486118757654.086781348751966.362026253 757674.88781944
752046.552084647757689.332479305752095.956219167757693.570883559
752230.255561709757696.835424352752383.400669557757716.445628114
#Sta/Elev= 30
9749.0641364.1519757.3241367.9039767.6621369.3439777.9991369.3059798.6751364.135
9819.3511357.9729829.6891356.1119839.8741355.4659860.1961350.1849870.3571349.388
9880.5181347.3879890.6781342.7979900.839 1339.87    99111337.9139931.0931337.248
 9941.131335.9259961.2031329.6239981.208 1325.099991.2081319.82410001.211316.624
10011.211321.45810031.211326.25310051.221324.99810061.231326.89510071.251327.668
10171.731331.14310181.831333.04610191.941333.11310212.161331.15810250.981333.757
#Mann= 3 , 0 , 0
9749.064    0.04       09749.064    0.04       010250.98    0.04       0
#XS Ineff= 2 , 0
       0                               0
Bank Sta=9749.064,10250.98
Exp/Cntr=0.3,0.1

Type RM Length L Ch R = 1 , 6322.73,149.927700,149.927700,149.927700
XS GIS Cut Line= 6
751881.051741956757794.170021692751999.818637794757825.183528321
752117.894765131757841.014713853752161.312699384757843.478603563
752285.249840107757836.887332748752377.180724935757844.723775571
#Sta/Elev= 30
9749.0241345.4399763.5451345.2619773.9551344.1599794.7761344.9499805.1861343.009
9825.8221340.4589836.0851338.0459846.3481337.3499856.6111333.6049866.8741331.443
9877.0681331.2249887.1991327.2899897.3291322.2849907.4591319.7169917.5891318.627
9937.7371319.5019947.8031320.517 9957.87  1322.69967.9361321.5789978.0021319.262
9988.0681315.7449998.1171314.31910018.151318.52410038.171320.98910068.261326.494
10088.311328.94510218.56 1327.7110228.621330.19110238.691333.68210250.951335.741
#Mann= 3 , 0 , 0
9749.024    0.04       09749.024    0.04       010250.95    0.04       0
#XS Ineff= 2 , 0
       09962.526                       0
Bank Sta=9749.024,10250.95
Exp/Cntr=0.3,0.1

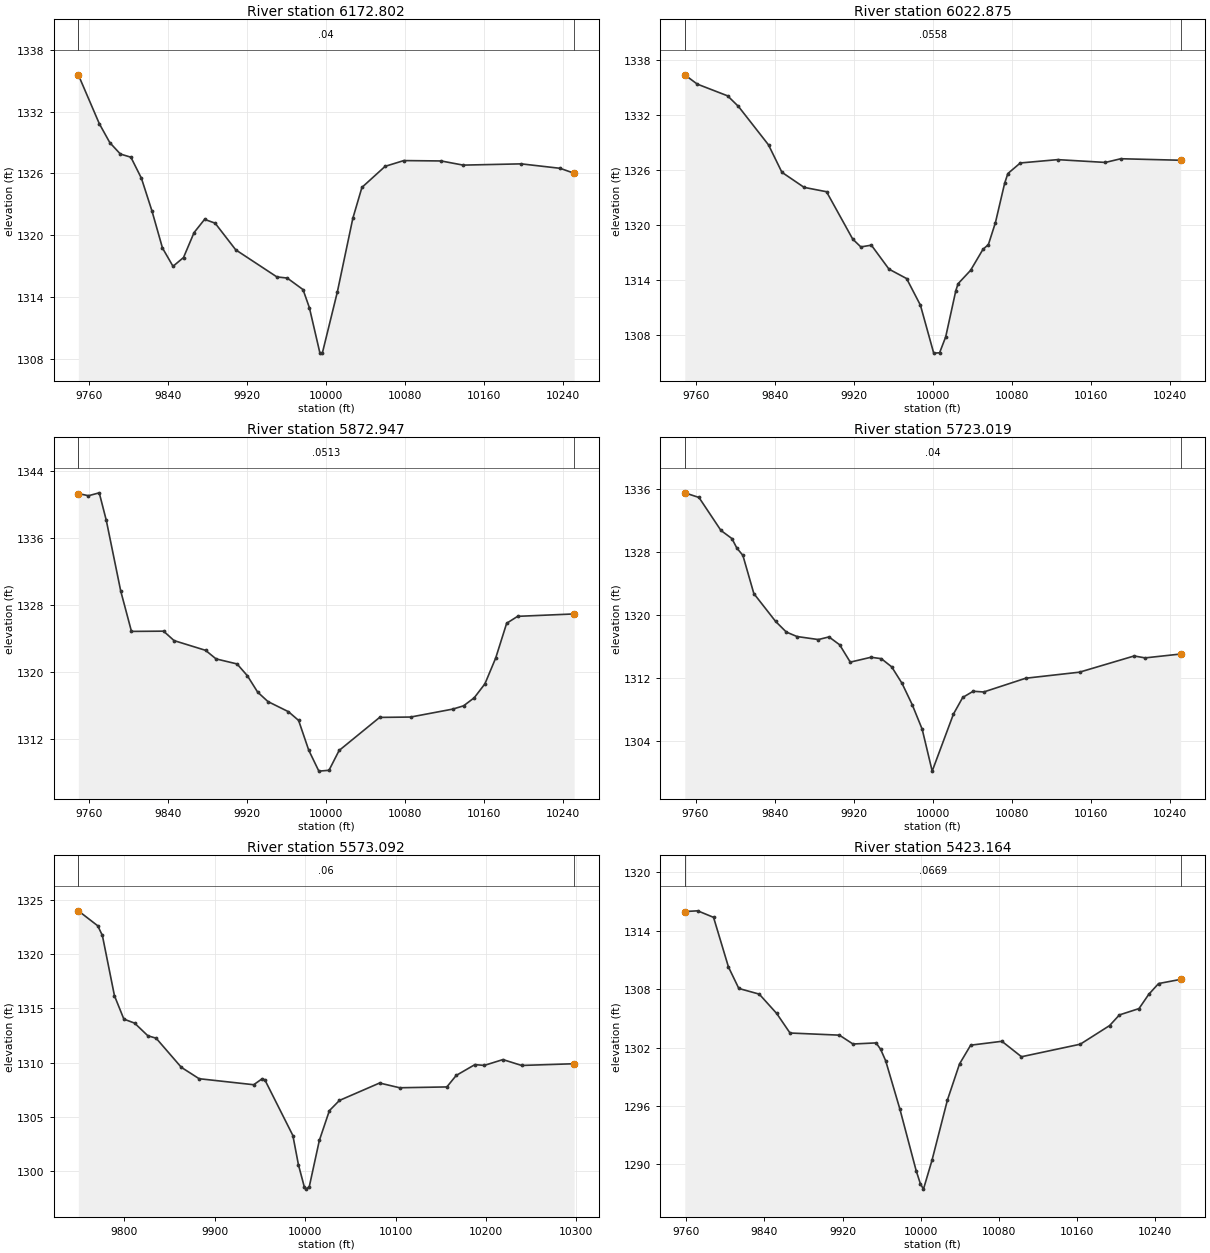
Type RM Length L Ch R = 1 ,6172.802,149.927600,149.927600,149.927600
XS GIS Cut Line= 6
 751925.07223945757880.290293276752056.057489464757928.409797015
752132.782967778757950.871825917752177.193866437757987.956053904
752220.393773507758014.651810065 752378.11890835758085.995634069
#Sta/Elev= 30
9749.1631335.5859770.3931330.8359781.046 1328.999791.6991327.8859802.3531327.575
9813.006 1325.53 9823.661322.3569834.3131318.7489844.9671316.969 9855.621317.824
9866.2731320.2469876.9271321.533 9887.581321.1649908.445 1318.579950.1231315.936
9960.5431315.8289976.5531314.7059982.9821312.9479993.6631308.5289996.189 1308.57
10011.221314.45210026.961321.63710036.141324.63910059.651326.68910078.541327.248
 10116.31327.21110138.591326.80710197.331326.92910236.661326.49710250.921326.016
#Mann= 3 , 0 , 0
9749.163    0.04       09749.163    0.04       010250.92    0.04       0
#XS Ineff= 2 , 0
       0                               0
Bank Sta=9749.163,10250.92
Exp/Cntr=0.3,0.1

Type RM Length L Ch R = 1 ,6022.875,149.927700,149.927700,149.927700
XS GIS Cut Line= 6
751815.604108928757929.761486064751906.623970046757971.387269554
751976.581112499758010.067908548752025.875494899758043.433938245
752145.206450236 758135.35959993752240.494574199758193.538516318
#Sta/Elev= 30
9749.0361336.3619761.632 1335.359792.3561334.0689803.3521332.9119833.7651328.717
9847.3371325.7259869.8161324.0779892.5081323.6029919.0431318.4289927.2561317.577
9937.8861317.7719955.7261315.1549973.5661314.1269987.5551311.217   100011305.986
10006.951306.02310013.131307.75610023.421312.81910025.721313.56810038.31 1315.02
10050.891317.31810056.351317.83110063.48 1320.2310072.811324.52610076.071325.588
10088.661326.74110126.421327.10510174.821326.79910190.381327.20310250.951327.037
#Mann= 3 , 0 , 0
9749.036  0.0558       09749.036  0.0558       010250.95  0.0558       0
#XS Ineff= 2 , 0
       0                               0
Bank Sta=9749.036,10250.95
Exp/Cntr=0.3,0.1

Type RM Length L Ch R = 1 ,5872.947,149.927700,149.927700,149.927700
XS GIS Cut Line= 6
751735.543667534 758103.87124669751810.075390359758135.727839628
751887.437112563 758163.60019614752025.822385318758197.616017922
752070.854396845758211.764406833752206.598425043758272.765860855
#Sta/Elev= 30
9749.0361341.3229759.319 1341.069770.1951341.4069777.3511338.1189791.9451329.697
 9802.821324.8749835.3241324.9049845.9541323.7769877.8411322.6169888.4711321.592
9909.7291320.992 9920.181319.5799930.5741317.6299940.9681316.5059961.7561315.293
9972.0131314.2569982.2641310.7069992.5141308.20510002.771308.30410013.021310.669
10054.031314.61410085.461314.65810128.191315.60810139.011315.99610149.821316.959
10160.641318.62610171.531321.69910182.621325.84410193.711326.67110250.951326.958
#Mann= 3 , 0 , 0
9749.036  0.0513       09749.036  0.0513       010250.95  0.0513       0
#XS Ineff= 2 , 0
       0                               0
Bank Sta=9749.036,10250.95
Exp/Cntr=0.3,0.1

Type RM Length L Ch R = 1 ,5723.019,149.927600,149.927600,149.927600
XS GIS Cut Line= 6
751702.072834771758232.089611292751854.090728211758299.834087304
751908.338737849758316.791834513751956.848395682758325.147597344
752020.697050334758347.709376162752167.179627145758415.453503495
#Sta/Elev= 30
 9749.111335.4529763.4671334.8629785.6791330.6849796.7851329.6559801.7731328.454
9807.8911327.5229818.9971322.6799841.0741319.1439851.8651317.8029862.6551317.235
9884.2361316.8529895.0271317.1859905.817 1316.199916.5791313.9899937.5341314.606
9948.0111314.4279958.4881313.3919968.9651311.2989979.2171308.6089989.3551305.486
9999.4871300.171   100211307.40710030.391309.513   100411310.297 10051.61310.204
10094.151311.94810148.591312.71610203.851314.769   102151314.52610250.911315.017
#Mann= 3 , 0 , 0
 9749.11    0.04       0 9749.11    0.04       010250.91    0.04       0
#XS Ineff= 2 , 0
       0                               0
Bank Sta=9749.11,10250.91
Exp/Cntr=0.3,0.1

Type RM Length L Ch R = 1 ,5573.092,149.927700,149.927700,149.927700
XS GIS Cut Line= 6
751672.632547021758313.380682334  751816.4697299758405.878872707
751880.225099534758452.478813425751881.854232639758453.638953671
751981.856671065758501.951040283752161.206448048758548.953050792
#Sta/Elev= 30
9749.0181324.003  9770.51322.6219775.6111321.7319788.9881316.165 9799.39 1314.01
9811.2791313.6399825.964 1312.479835.057 1312.25 9862.941309.5619882.615 1308.51
9942.9821307.9559952.433 1308.519955.369  1308.49986.3261303.2699992.5281300.552
    9999 1298.52   10001 1298.3210004.491298.553 10015.61302.81210026.711305.562
10037.811306.50410082.231308.11210104.451307.67510156.661307.751   101671308.812
10187.671309.81110198.011309.73710218.691310.27510239.361309.73310297.471309.892
#Mann= 3 , 0 , 0
9749.018    0.06       09749.018    0.06       010297.47    0.06       0
#XS Ineff= 2 , 0
       0                               0
Bank Sta=9749.018,10297.47
Exp/Cntr=0.3,0.1

Type RM Length L Ch R = 1 ,5423.164,41.053900,41.053900,41.053900
XS GIS Cut Line= 6
751592.234741777758416.605284333751702.438827306758507.103470966
751748.718477517758542.073941812751792.235216647758571.579292655
751829.000553161758598.505290613752037.516946673758582.349216163
#Sta/Elev= 30
9758.3631315.9689771.5911316.0399787.8211315.3699803.1051310.269  9813.71308.068
 9834.621307.4869852.5191305.4989866.1341303.4939916.7071303.2739930.6491302.364
9954.3091302.477 9958.97 1301.829964.1271300.6449978.7411295.6639995.358 1289.36
9999.7321287.99910002.851287.46210011.561290.41410027.381296.60910039.771300.316
10051.191302.243 10083.21302.64210103.261301.05610163.441302.34210193.531304.257
10203.56 1305.3510223.62    130610233.651307.46810243.681308.57110266.27    1309
#Mann= 3 , 0 , 0
9758.363  0.0669       09758.363  0.0669       010266.27  0.0669       0
#XS Ineff= 2 , 0
       09954.813        10072.26       0
Bank Sta=9758.363,10266.27
Exp/Cntr=0.3,0.1

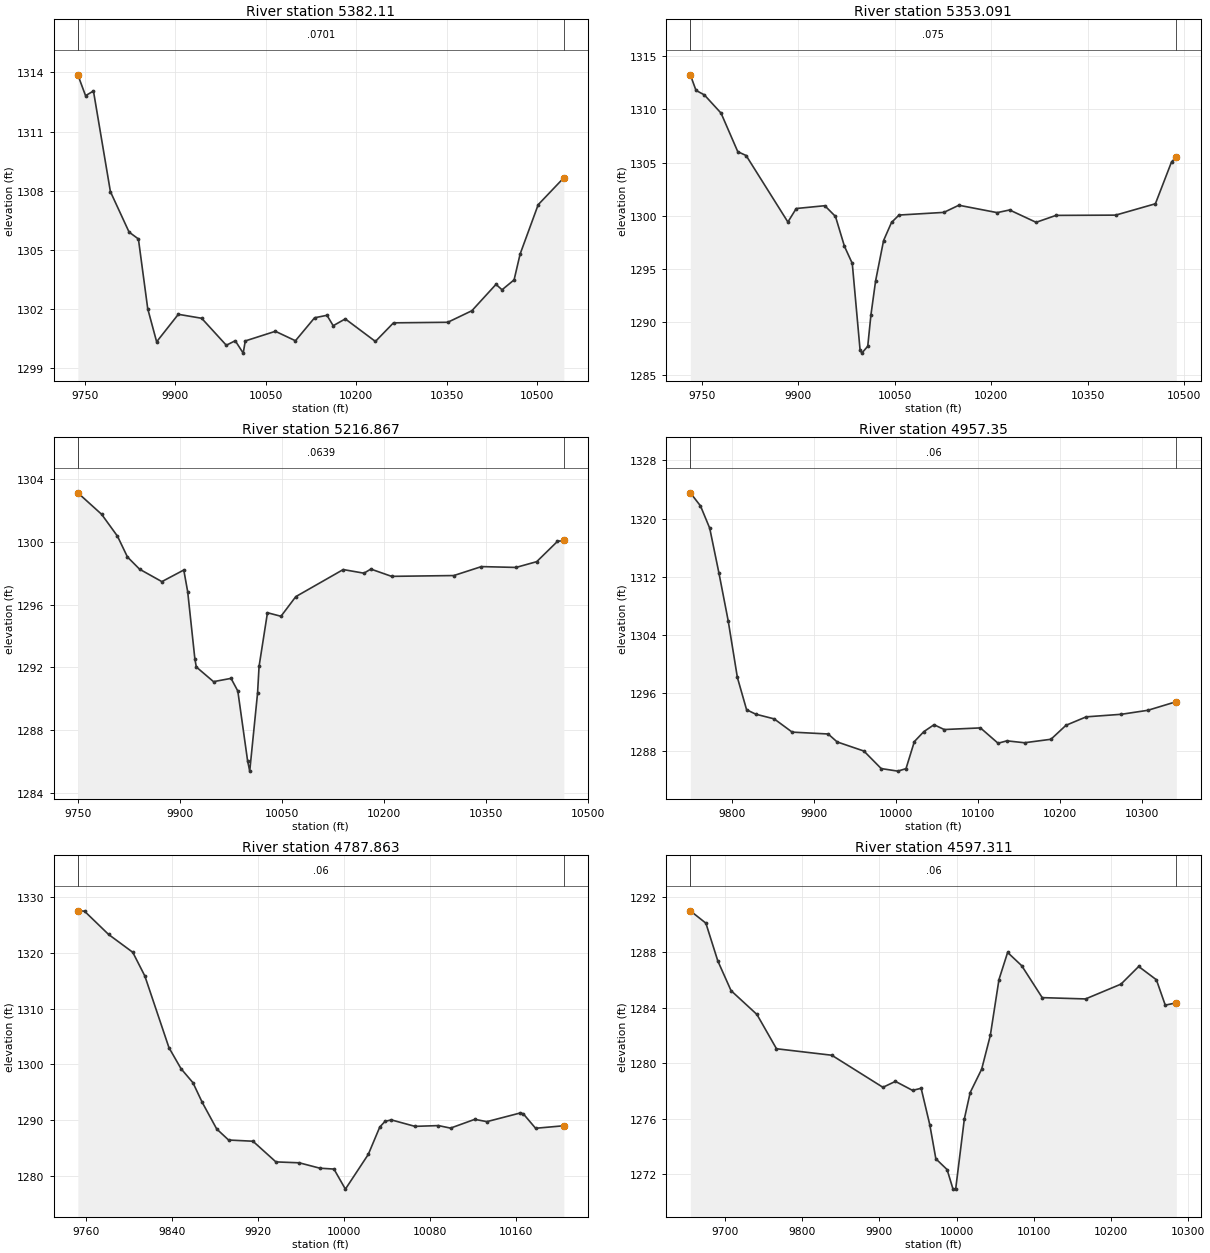
Type RM Length L Ch R = 1 , 5382.11,29.019400,29.019400,29.019400
XS GIS Cut Line= 6
751545.232731223 758440.10628958751656.145543337758533.971706793
751742.601527393758586.087697193751834.858229011758655.435016543
751896.775478452758670.295156389752277.474579364758666.458077103
#Sta/Elev= 30
9738.5221313.8789751.3171312.8219764.4181313.0589792.5361307.9599823.495 1305.91
9838.9751305.5619854.4551302.0259869.221 1300.359905.1841301.7439943.9251301.542
9984.7721300.1759999.6041300.40410012.791299.77610016.251300.39410066.181300.882
10099.461300.40310131.181301.56710151.751301.69310162.041301.16510182.09 1301.51
10232.091300.36810262.091301.311 10352.11301.339 10392.11301.925 10432.11303.261
 10442.11302.985 10462.11303.488 10472.11304.797 10502.11307.29910544.581308.661
#Mann= 3 , 0 , 0
9738.522  0.0701       09738.522  0.0701       010544.58  0.0701       0
#XS Ineff= 2 , 0
       09956.652        10071.65       0
Bank Sta=9738.522,10544.58
Exp/Cntr=0.3,0.1

Type RM Length L Ch R = 1 ,5353.091,136.223500,136.223500,136.223500
XS GIS Cut Line= 6
751528.208471209758452.799150184751659.327132314758561.607841104
751705.606782496 758596.57831198751774.501041383758644.669513226
751916.278878838758729.023938105752186.572459668 758796.80916214
#Sta/Elev= 30
9731.8181313.2569740.6441311.7929753.6381311.3689779.6281309.6519805.6181306.027
9818.6121305.6649883.5861299.4099896.5811300.6789941.0051300.9429957.5931299.935
9971.6171297.1199983.7611295.5139995.9041287.3699998.5981287.07210007.831287.721
 10012.81290.67110020.081293.87810032.481297.66710044.831299.36910056.471300.063
10126.291300.31410149.561300.98610209.231300.29110228.531300.54110269.771299.379
 10300.71300.03110393.481300.05610455.341301.12410480.451305.06210487.891305.534
#Mann= 3 , 0 , 0
9731.818   0.075       09731.818   0.075       010487.89   0.075       0
#XS Ineff= 2 , 0
       0                10070.11       0
Bank Sta=9731.818,10487.89
Exp/Cntr=0.3,0.1

Type RM Length L Ch R = 1 ,5216.867,259.517100,259.517100,259.517100
XS GIS Cut Line= 6
751509.109685242758537.381563157751644.045849174758710.561911359
751664.811795831758732.799688354751698.665932566758768.465064958
751725.858923703758800.003573418752094.215091914758869.678277999
#Sta/Elev= 30
9749.0311303.1289784.0431301.7599807.4251300.3619822.0751299.0379839.9651298.258
9872.7831297.4659905.0461298.2059910.8141296.8189921.3161292.5619923.4921292.021
9948.8461291.0859974.6461291.2959984.6241290.487    99991286.04410002.151285.379
10013.711290.36210015.911292.05710028.271295.48110048.181295.25510070.011296.508
10139.831298.23410170.371298.00310180.541298.26510211.081297.80110302.671297.852
10343.381298.42310394.27 1298.37 10424.81298.73810455.331300.03110464.711300.101
#Mann= 3 , 0 , 0
9749.031  0.0639       09749.031  0.0639       010464.71  0.0639       0
#XS Ineff= 2 , 0
       0                10081.75       0
Bank Sta=9749.031,10464.71
Exp/Cntr=0.3,0.1

Type RM Length L Ch R = 1 , 4957.35,169.487500,169.487500,169.487500
XS GIS Cut Line= 6
 751333.28492632758603.978451083751422.121761066758789.143183234
 751431.18710723758816.559054207751436.806632936758858.873469792
751477.203505486758913.837079868751707.265978038759004.130415872
#Sta/Elev= 30
9749.0811323.533 9761.471321.7349772.7111318.6689783.9521312.5029795.193 1305.96
9806.4341298.1419817.6741293.6959828.9151293.0879851.2931292.4439873.2231290.622
9917.0841290.3659928.0491289.2749960.6911288.0189981.7561285.60910001.951285.257
10011.981285.59710022.191289.32410033.751290.69110046.161291.63810058.571290.978
10102.741291.20210124.221289.09310134.961289.42210156.45 1289.1610188.681289.638
10207.031291.56210231.651292.72210274.621293.07610306.851293.62510341.511294.811
#Mann= 3 , 0 , 0
9749.081    0.06       09749.081    0.06       010341.51    0.06       0
#XS Ineff= 2 , 0
       0                10095.04       0
Bank Sta=9749.081,10341.51
Exp/Cntr=0.3,0.1

Type RM Length L Ch R = 1 ,4787.863,190.551400,190.551400,190.551400
XS GIS Cut Line= 6
751173.265425921758669.478656655751248.589222945758823.160560697
751269.400809387758872.667378428751290.018373598758929.638283571
751311.597554816758978.256961242751364.907904762759077.724518157
#Sta/Elev= 30
9752.6011327.5249758.7911327.4629781.2151323.2839803.6381320.093 9814.851315.845
9837.2731302.9919848.4851299.2219859.5361296.7179868.1911293.1779881.6251288.418
9892.6691286.4389915.3131286.2229936.6131282.5169958.3081282.3549977.4731281.388
9990.5641281.23110001.181277.63510022.451283.85910033.121288.76310038.071289.795
10043.931290.04410065.811288.88610087.691289.02510098.851288.57210121.381290.144
10132.651289.732 10163.81291.29310166.441291.148 10177.91288.54310204.131288.996
#Mann= 3 , 0 , 0
9752.601    0.06       09752.601    0.06       010204.13    0.06       0
#XS Ineff= 2 , 0
       0                10087.59       0
Bank Sta=9752.601,10204.13
Exp/Cntr=0.3,0.1

Type RM Length L Ch R = 1 ,4597.311,115.787200,115.787200,115.787200
XS GIS Cut Line= 5
750836.896257252758822.651078597750987.896761417758939.924753994
 751080.13870278758983.985001802751270.416480541759079.818335146
751377.479763031759139.942543045
#Sta/Elev= 30
9655.3581290.992 9675.491290.1019690.9421287.3749708.096 1285.239741.5891283.512
9766.9121281.0369838.5211280.5689904.7271278.2539920.9151278.6819943.0791278.031
9954.2171278.1829965.4141275.5489973.2621273.0929987.8071272.3159995.4931270.903
9999.0041270.942 10010.21275.98510017.721277.87610032.591279.56310043.791281.999
10054.99 1286.0310066.181287.98910084.421287.03210110.971284.72610167.081284.632
10212.961285.70110235.891286.97410258.831286.015 10270.31284.18310284.611284.352
#Mann= 3 , 0 , 0
9655.358    0.06       09655.358    0.06       010284.61    0.06       0
#XS Ineff= 2 , 0
       09932.654        10036.57       0
Bank Sta=9655.358,10284.61
Exp/Cntr=0.3,0.1

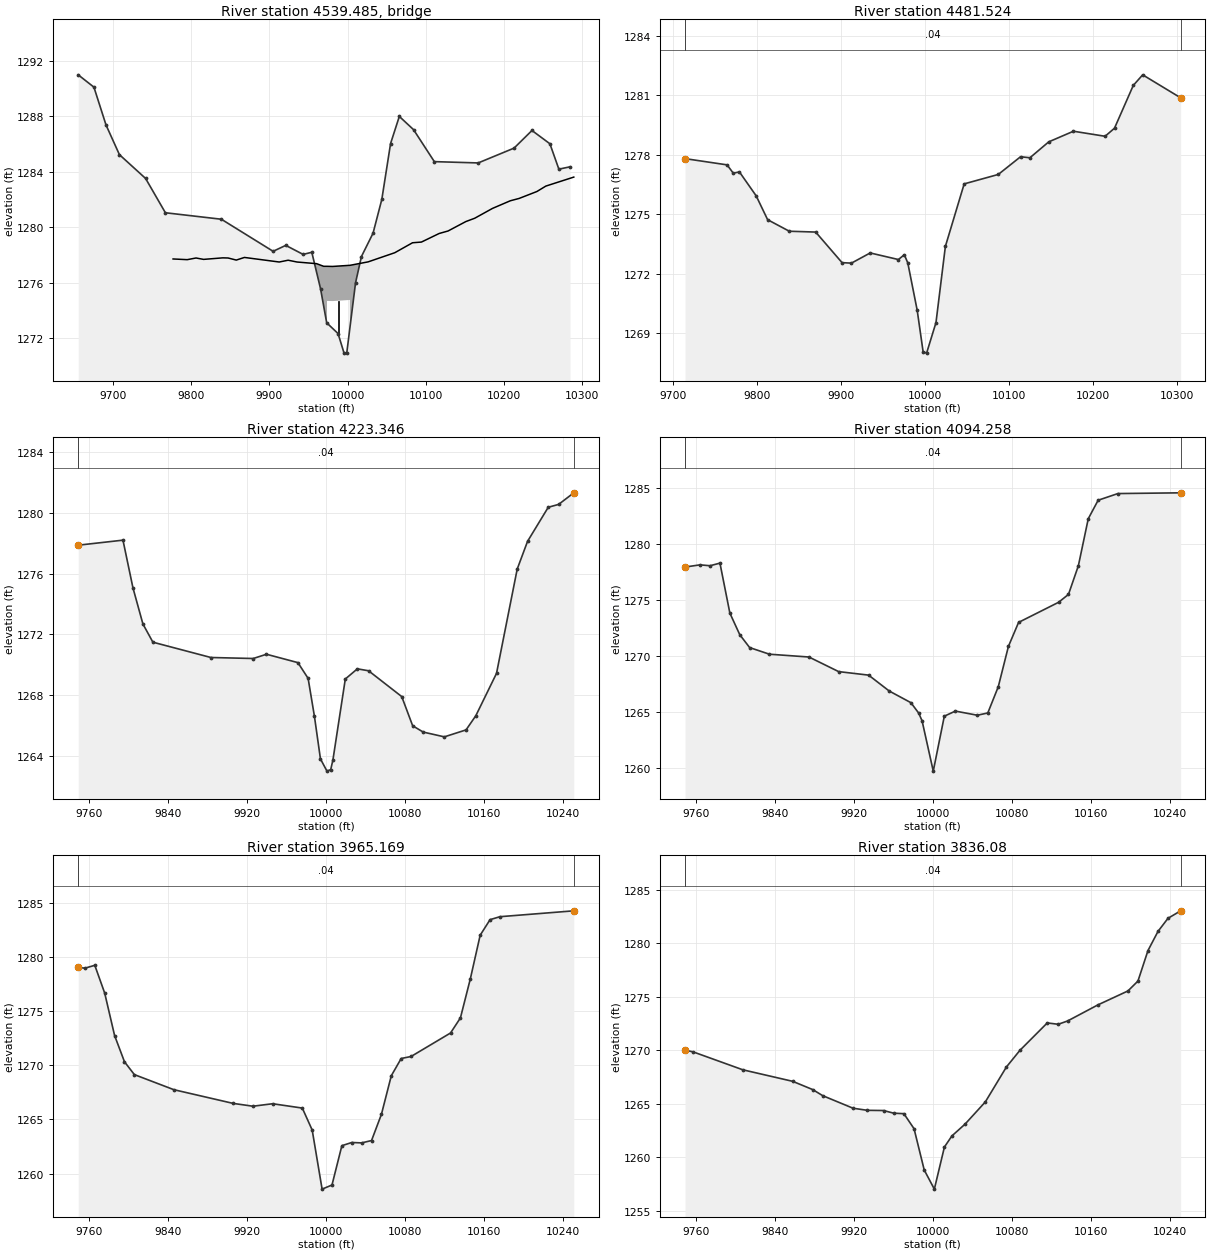
Type RM Length L Ch R = 3 ,4539.485,,,
BEGIN DESCRIPTION:
END DESCRIPTION:
Bridge Culvert--1,0,-1,-1, 0
Deck Dist Width WeirC Skew NumUp NumDn MinLoCord MaxHiCord MaxSubmerge Is_Ogee
45.918550,23.950100,2.6,0, 33, 32, , , 0.95, 0, 0,0,,
 9776.74 9794.86 9806.11 9815.77 9840.37 9847.13 9857.59 9868.04 9912.56 9923.93
 9935.30 9960.42 9969.40 9973.67 9973.67 9980.7710002.4810002.8710002.8710026.24
10060.3410083.0810094.4510117.1810128.5510151.2910162.6510185.3910208.1310219.49
10242.2310253.6010289.39
 1277.70 1277.65 1277.77 1277.67 1277.78 1277.77 1277.62 1277.81 1277.48 1277.61
 1277.48 1277.36 1277.17 1277.17 1277.17 1277.16 1277.24 1277.24 1277.24 1277.49
 1278.15 1278.87 1278.92 1279.54 1279.72 1280.40 1280.64 1281.35 1281.90 1282.07
 1282.57 1282.96 1283.61
  277.70  277.65  277.77  277.67  277.78  277.77  277.62  277.81  277.48  277.61
  277.48  277.36  277.17  277.17 1274.67 1274.66 1274.74 1274.74  277.24  277.49
  278.15  278.87  278.92  279.54  279.72  280.40  280.64  281.35  281.90  282.07
  282.57  282.96  283.61
 9776.74 9794.86 9806.11 9815.77 9840.37 9847.13 9857.59 9868.04 9912.56 9923.93
 9935.30 9960.42 9969.40 9980.77 9994.70 9994.7010023.5010023.9010023.9010060.34
10083.0810094.4510117.1810128.5510151.2910162.6510185.3910208.1310219.4910242.23
10253.6010289.39
 1277.70 1277.65 1277.77 1277.67 1277.78 1277.77 1277.62 1277.81 1277.48 1277.61
 1277.48 1277.36 1277.17 1277.16 1277.19 1277.19 1277.48 1277.48 1277.48 1278.15
 1278.87 1278.92 1279.54 1279.72 1280.40 1280.64 1281.35 1281.90 1282.07 1282.57
 1282.96 1283.61
  277.70  277.65  277.77  277.67  277.78  277.77  277.62  277.81  277.48  277.61
  277.48  277.36  277.17  277.16  277.19 1274.69 1274.98 1274.98  277.48  278.15
  278.87  278.92  279.54  279.72  280.40  280.64  281.35  281.90  282.07  282.57
  282.96  283.61
Pier Skew, UpSta & Num, DnSta & Num=  ,9988.27, 2 ,10009.30, 2 , 0 , 0 , 0 ,,
    2.00    2.00
  277.17 1277.17
    2.00    2.00
  277.32 1277.32
BR Coef=-1 , 0 , 0 ,, 0 ,,,0.8,0,1,0,
WSPro=,,,, 1 ,,,, 0 ,,,, 0 ,,,,-1 ,-1 ,-1 , 0 , 0 , 0 , 0 , 0
BC Design=,, 0 ,, 0 ,,,,,,

Type RM Length L Ch R = 1 ,4481.524,258.177600,258.177600,258.177600
XS GIS Cut Line= 5
750812.990883082758950.943930268750900.230003744759031.991593465
750965.383655488759052.038870916 751293.16143328759215.927759811
751324.390461057759233.905301049
#Sta/Elev= 30
 9714.12  1277.89764.1561277.485 9771.461277.0699778.8481277.1289798.7591275.922
9812.4091274.7179838.1881274.1359869.5761274.0939900.9641272.5499912.1161272.525
9934.4771273.0399968.0181272.7069975.0681272.9499979.1981272.5359990.3791270.146
9997.429 1268.0510001.561267.98210012.741269.52410023.921273.36910046.281276.525
10086.871277.00110113.361277.89510124.541277.844 10146.91278.64610176.311279.183
10213.991278.92810225.171279.33610247.531281.49610258.71 1282.0310303.87 1280.87
#Mann= 3 , 0 , 0
 9714.12    0.04       0 9714.12    0.04       010303.87    0.04       0
#XS Ineff= 2 , 0
       09955.588        10050.89       0
Bank Sta=9714.12,10303.87
Exp/Cntr=0.3,0.1

Type RM Length L Ch R = 1 ,4223.346,129.088800,129.088800,129.088800
XS GIS Cut Line= 6
750750.196051242758920.097205672750768.671043518759053.190507524
750781.433521361759107.945034801750794.865839755759136.541906752
750852.030129796 759224.63240954750907.584684263759389.671026246
#Sta/Elev= 30
9749.115 1277.869794.4491278.1919804.545 1275.06 9814.641272.6849824.7361271.487
9883.4851270.4819926.3171270.4159939.7581270.6949971.5771270.1449981.9111269.109
9988.2841266.6239994.3941263.818   100011263.01510004.781263.11410007.021263.747
10019.571269.06810031.781269.73610043.111269.60910076.691267.91310087.771265.994
10098.461265.58110119.841265.26710141.811265.724 10151.71266.65510172.661269.437
10193.61 1276.2910204.091278.11510225.051280.35310235.53 1280.54 10250.91281.301
#Mann= 3 , 0 , 0
9749.115    0.04       09749.115    0.04       0 10250.9    0.04       0
#XS Ineff= 2 , 0
       0                10040.67       0
Bank Sta=9749.115,10250.9
Exp/Cntr=0.3,0.1

Type RM Length L Ch R = 1 ,4094.258,129.088900,129.088900,129.088900
XS GIS Cut Line= 6
750722.102104234 758919.81779746750727.512563596759082.549326759
750718.264663407759123.724318453750679.577924784759201.689065052
750664.472901393759253.373673978750662.914548879759408.368203227
#Sta/Elev= 30
9749.0541277.9649764.3071278.1599774.354 1278.089784.4011278.3149794.4481273.846
9804.4771271.9159814.4921270.7639834.5221270.171 9874.54 1269.929904.5941268.616
 9934.951268.3019955.8241266.8819977.765 1265.849985.6521264.9099989.1031264.215
10000.421259.71910011.621264.63210022.821265.08610045.031264.71610055.651264.918
10066.261267.26310076.541270.87110086.831273.01610127.351274.81310137.361275.519
10147.371278.08110157.391282.283 10167.41283.937 10187.41284.53210250.931284.598
#Mann= 3 , 0 , 0
9749.054    0.04       09749.054    0.04       010250.93    0.04       0
#XS Ineff= 2 , 0
       09940.543        10082.88       0
Bank Sta=9749.054,10250.93
Exp/Cntr=0.3,0.1

Type RM Length L Ch R = 1 ,3965.169,129.088800,129.088800,129.088800
XS GIS Cut Line= 6
 750575.27348107758878.215849634750580.359565046758960.373777014
 750581.29245162759023.924849701750572.820167231759256.666776085
750574.378350515759311.778626104750579.628206994759379.594365082
#Sta/Elev= 30
9749.0191279.0399755.8161278.9549765.835 1279.229775.8551276.6579785.874 1272.74
9795.8931270.3149805.912 1269.139845.9621267.7379905.9711266.4739925.9771266.213
9945.9831266.4419976.0141266.0419986.032 1264.019996.0511258.55910006.071258.939
10016.08 1262.57 10026.11262.86310036.111262.82710046.131263.04410056.141265.462
10066.151269.02710076.151270.61710086.151270.80210126.161272.97310136.161274.366
10146.17 1277.9610156.17    128210166.171283.43410176.181283.70710250.981284.249
#Mann= 3 , 0 , 0
9749.019    0.04       09749.019    0.04       010250.98    0.04       0
#XS Ineff= 2 , 0
       09963.168                       0
Bank Sta=9749.019,10250.98
Exp/Cntr=0.3,0.1

Type RM Length L Ch R = 1 , 3836.08,258.177600,258.177600,258.177600
XS GIS Cut Line= 6
750406.417389502758896.835838479750416.303154836758983.954216121
750426.587748641759044.609212192750453.387957657759157.109167035
750484.783137421759265.718772319750507.289496253759387.624953843
#Sta/Elev= 30
9749.0461270.0029757.2631269.8379807.5831268.162 9858.071267.0849878.3551266.312
9888.4981265.7429919.2341264.568 9933.721264.3729950.1141264.3539960.4081264.104
9970.7021264.0589980.9951262.6519991.2891258.79210001.541257.00210011.751260.943
10019.361261.98110032.631263.08110053.19 1265.1610074.511268.42310088.231269.985
10115.911272.54610126.99 1272.4210136.471272.72810167.091274.22810197.611275.537
10207.751276.46110217.891279.31210228.031281.10210238.17 1282.3310250.98 1283.03
#Mann= 3 , 0 , 0
9749.046    0.04       09749.046    0.04       010250.98    0.04       0
#XS Ineff= 2 , 0
       09957.066                       0
Bank Sta=9749.046,10250.98
Exp/Cntr=0.3,0.1