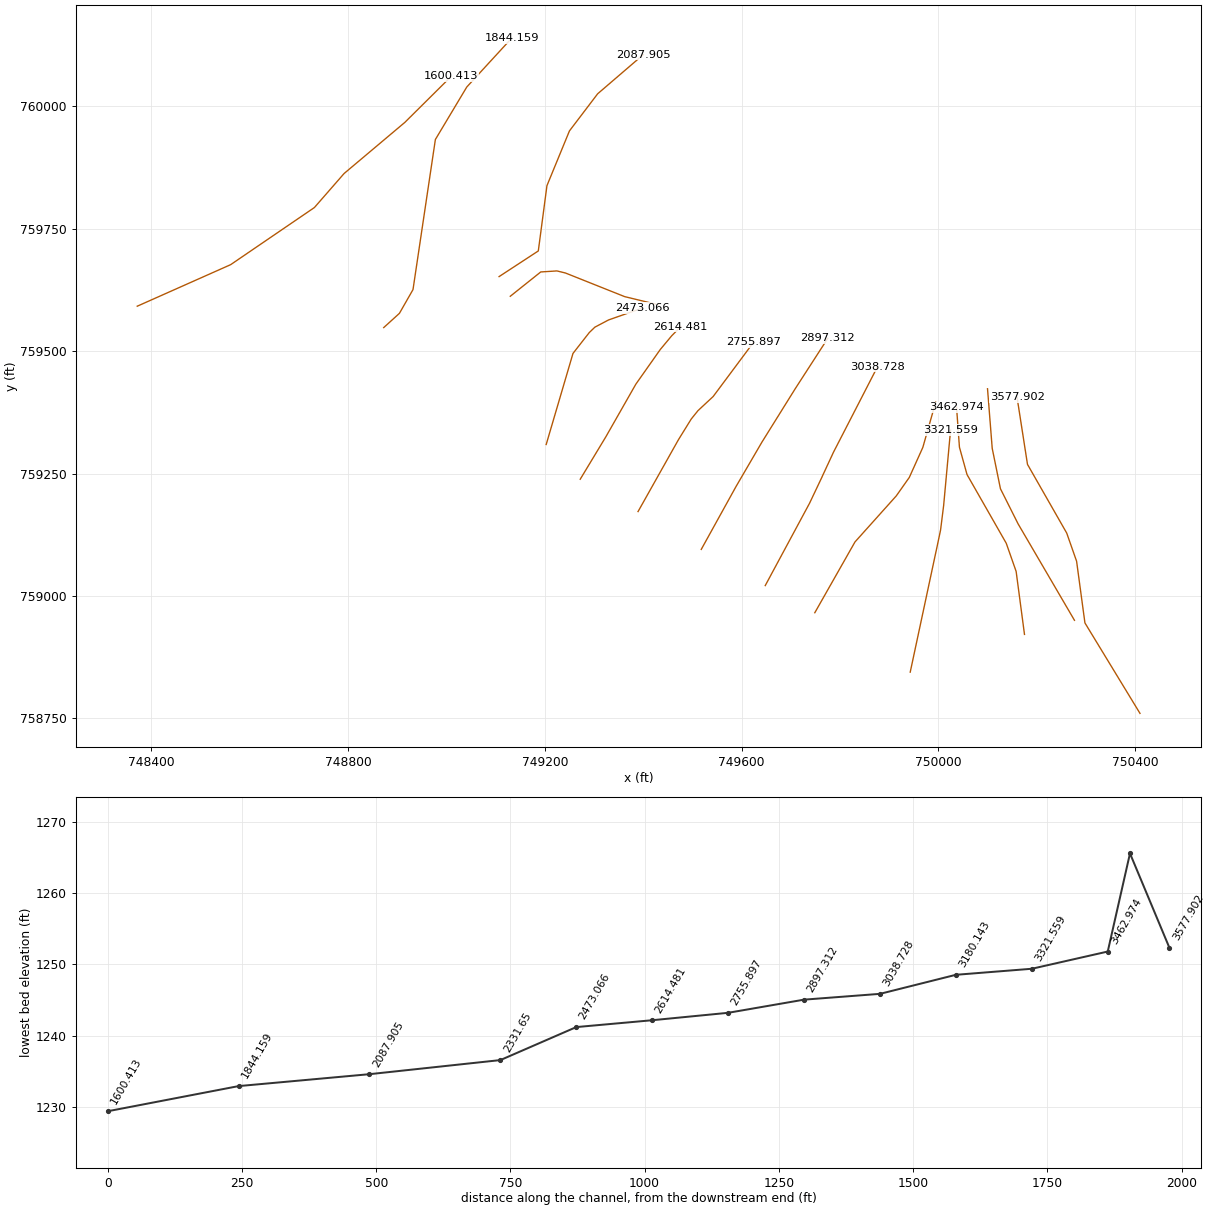
HEC-RAS study 14322_ras.prj: 14322

--- 14322_ras.g01 (geometry) --- (continued)

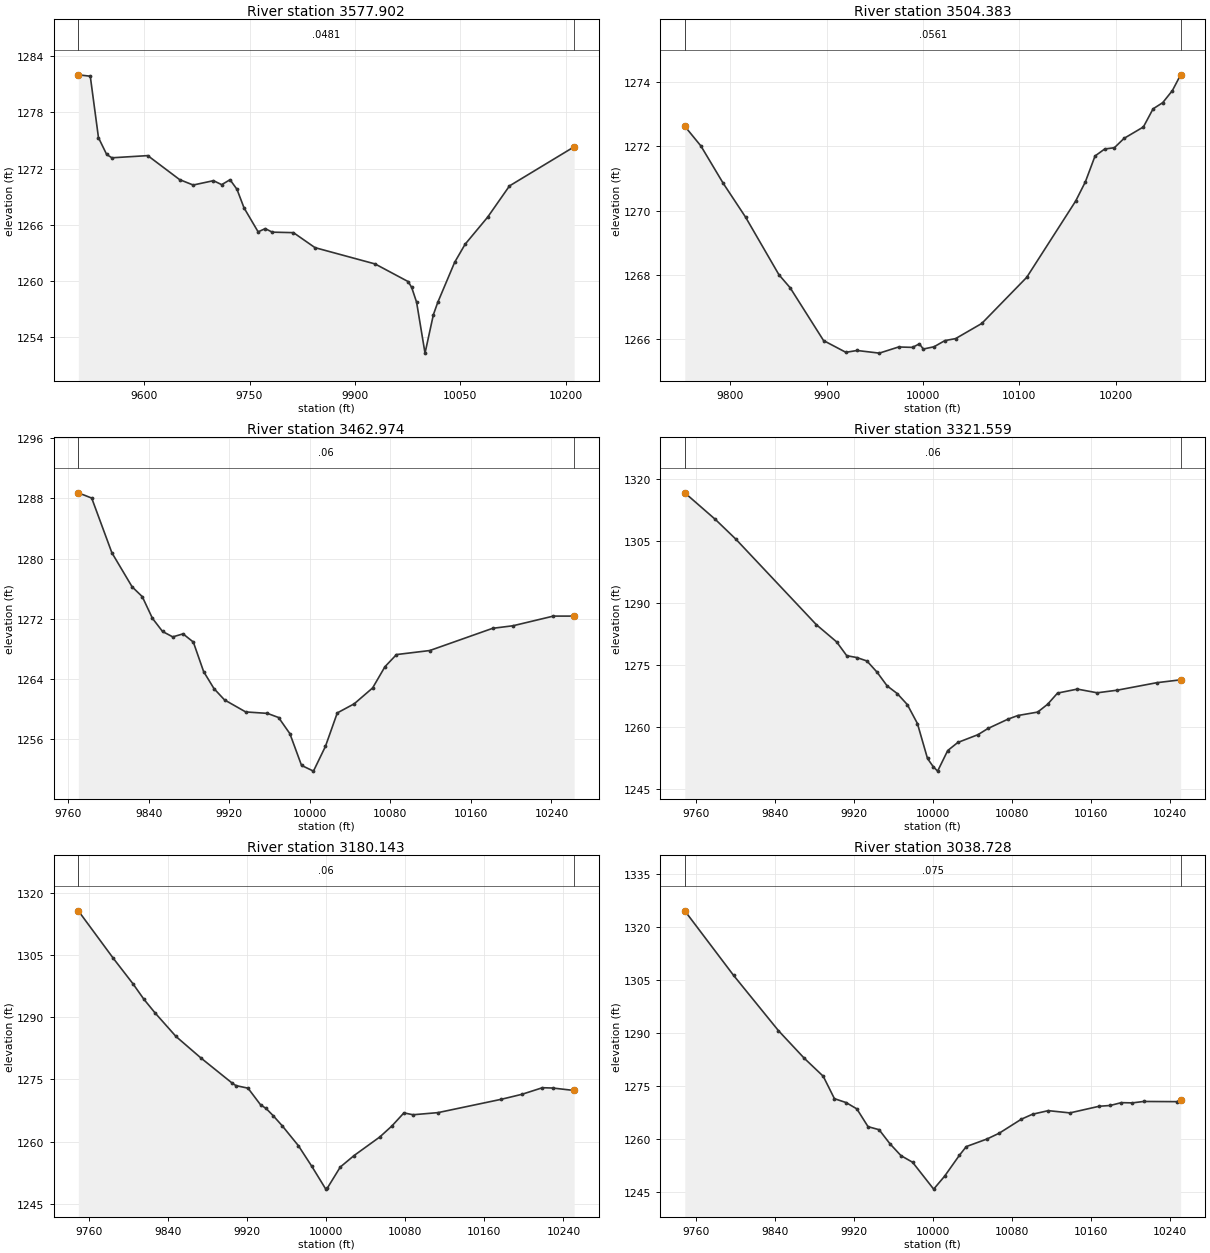
Type RM Length L Ch R = 1 ,3577.902,73.519700,73.519700,73.519700
XS GIS Cut Line= 6
750409.763108641758760.462098151750297.829371989758945.175238907
750280.884273976759071.209956422750260.776595145759128.755787343
750181.043300033759269.029913664750159.758558333759406.480248392
#Sta/Elev= 30
9506.2491282.0129523.2481281.8659534.941  1275.39546.6331273.508 9554.031273.156
9605.0971273.3899650.5081270.8259669.803 1270.25 9698.641270.7149710.333 1270.29
9722.2311270.8159732.1061269.7969742.1571267.8129762.2591265.249 9772.311265.598
9782.3611265.2199812.5571265.1669843.2061263.5669928.8261261.8249975.889 1259.94
9980.8691259.3169987.8471257.7419999.8461252.30710011.781256.41910017.921257.713
10042.061262.004 10056.91263.92710089.011266.82110120.111270.15610212.18 1274.33
#Mann= 3 , 0 , 0
9506.249  0.0481       09506.249  0.0481       010212.18  0.0481       0
#XS Ineff= 2 , 0
       09915.831                       0
Bank Sta=9506.249,10212.18
Exp/Cntr=0.3,0.1

Type RM Length L Ch R = 1 ,3504.383,41.408600,41.408600,41.408600
XS GIS Cut Line= 5
 750276.54791081758950.557093963750161.893871427759147.618724272
 750126.06448403759219.277498946750109.344103307759301.685089782
750099.789600044759423.505006686
#Sta/Elev= 30
9752.8221272.6269769.5311272.014 9792.671270.8539815.8091269.8049850.5171268.008
9862.0871267.6069896.7951265.9629919.9341265.5979931.5031265.6549954.6421265.572
9974.6341265.7639989.0631265.7519996.2251265.86110000.241265.69910011.42 1265.77
 10022.61265.96110033.781266.02410060.931266.49510107.58 1267.9310158.371270.303
 10168.41270.89910178.431271.70210188.46 1271.9210198.491271.95910208.52 1272.25
10228.581272.60510238.621273.16810248.651273.36110258.681273.73710267.211274.226
#Mann= 3 , 0 , 0
9752.822  0.0561       09752.822  0.0561       010267.21  0.0561       0
#XS Ineff= 2 , 0
       0 9918.19                       0
Bank Sta=9752.822,10267.21
Exp/Cntr=0.3,0.1

Type RM Length L Ch R = 1 ,3462.974,141.415500,141.415500,141.415500
XS GIS Cut Line= 6
750174.947756577758921.746635867750157.967607297759050.376623071
 750137.85992845759107.922453985750058.126633372759248.196580317
750042.689562405759304.165537246750036.841891649759385.646915029
#Sta/Elev= 30
9769.9651288.7229783.2441288.0269803.291 1280.779823.4061276.2489833.4871274.947
9843.5681272.0749853.6491270.3229863.7761269.6089873.9921270.0079884.209 1268.92
9894.4251265.0069904.7451262.7419915.1851261.246 9936.231259.6499957.7891259.458
9968.8921258.908 9980.131256.7659991.6971252.55610003.551251.79410015.411255.067
10027.221259.51810044.051260.72810062.311262.83110074.571265.64910086.031267.261
10119.111267.79610181.561270.74410201.741271.08210241.881272.36510262.541272.364
#Mann= 3 , 0 , 0
9769.965    0.06       09769.965    0.06       010262.54    0.06       0
#XS Ineff= 2 , 0
       0                               0
Bank Sta=9769.965,10262.54
Exp/Cntr=0.3,0.1

Type RM Length L Ch R = 1 ,3321.559,141.415500,141.415500,141.415500
XS GIS Cut Line= 6
749942.627457765758844.668844711749994.668151953 759089.17933387
749995.136669667759091.123682386750004.313227775759134.735741803
750010.615177453759185.315449941750024.658499586759339.109337386
#Sta/Elev= 30
9749.0131316.6089780.0231310.1659800.4711305.4699882.263 1284.749902.7111280.603
9912.9351277.2689923.1591276.8159933.3831275.9859943.6071273.2969953.8311269.973
9964.0551268.1179974.2791265.4549984.5031260.8819994.7271252.42710000.421250.482
10004.961249.37510015.181254.348 10025.41256.29810045.831258.18310055.911259.674
10076.071261.91710086.141262.80410106.261263.641 10116.31265.52610126.351268.226
10146.431269.19310166.511268.298 10186.61268.92310226.761270.73610250.971271.435
#Mann= 3 , 0 , 0
9749.013    0.06       09749.013    0.06       010250.97    0.06       0
#XS Ineff= 2 , 0
       0                               0
Bank Sta=9749.013,10250.97
Exp/Cntr=0.3,0.1

Type RM Length L Ch R = 1 ,3180.143,141.415500,141.415500,141.415500
XS GIS Cut Line= 6
749748.665195497 758966.05160739749830.323743949759110.568447877
749914.269674454759204.613078315749940.850352813 759242.51479006
749968.245219109759303.573109109749994.371330516759396.023947574
#Sta/Elev= 30
9749.0921315.6969784.6311304.1919804.208 1298.159815.4681294.3519826.7281291.063
9847.8861285.3829873.417 1280.139905.0551274.0649908.6591273.5099920.8111272.894
9933.4711268.8969939.131 1267.999946.1321266.2929955.4361263.8159971.7951259.015
9985.4371254.0069999.5221248.528   100011248.745 10014.2 1253.8610028.161256.637
10054.171261.11410066.391263.762 10078.61266.93110087.781266.47810113.111266.993
10177.261270.21610198.081271.41710218.781273.00410229.13 1272.9310250.881272.337
#Mann= 3 , 0 , 0
9749.092    0.06       09749.092    0.06       010250.88    0.06       0
#XS Ineff= 2 , 0
       0                               0
Bank Sta=9749.092,10250.88
Exp/Cntr=0.3,0.1

Type RM Length L Ch R = 1 ,3038.728,141.415500,141.415500,141.415500
XS GIS Cut Line= 6
749647.890264277 759021.47692813749737.991469089 759189.64195222
  749763.2689157759243.174268743749764.053793069 759245.01382508
749786.686521572759293.966957028749876.111610425759468.439524629
#Sta/Elev= 30
9749.0181324.6539798.3951306.3829843.7741290.7439869.9431282.9179889.1541277.817
9900.4991271.4669912.2911270.3649923.1891268.5779934.534 1263.549945.7251262.679
9956.7841258.6779967.8431255.3459979.6341253.46210000.981245.853   100121249.501
10027.081255.45810034.041257.90610054.931260.04310067.33 1261.69 10089.81265.665
10101.041267.05910117.011268.07410138.931267.43610168.461269.312 10179.71269.539
10190.941270.33910202.171270.27510213.411270.67310247.121270.62310250.991271.074
#Mann= 3 , 0 , 0
9749.018   0.075       09749.018   0.075       010250.99   0.075       0
#XS Ineff= 2 , 0
       0                               0
Bank Sta=9749.018,10250.99
Exp/Cntr=0.3,0.1

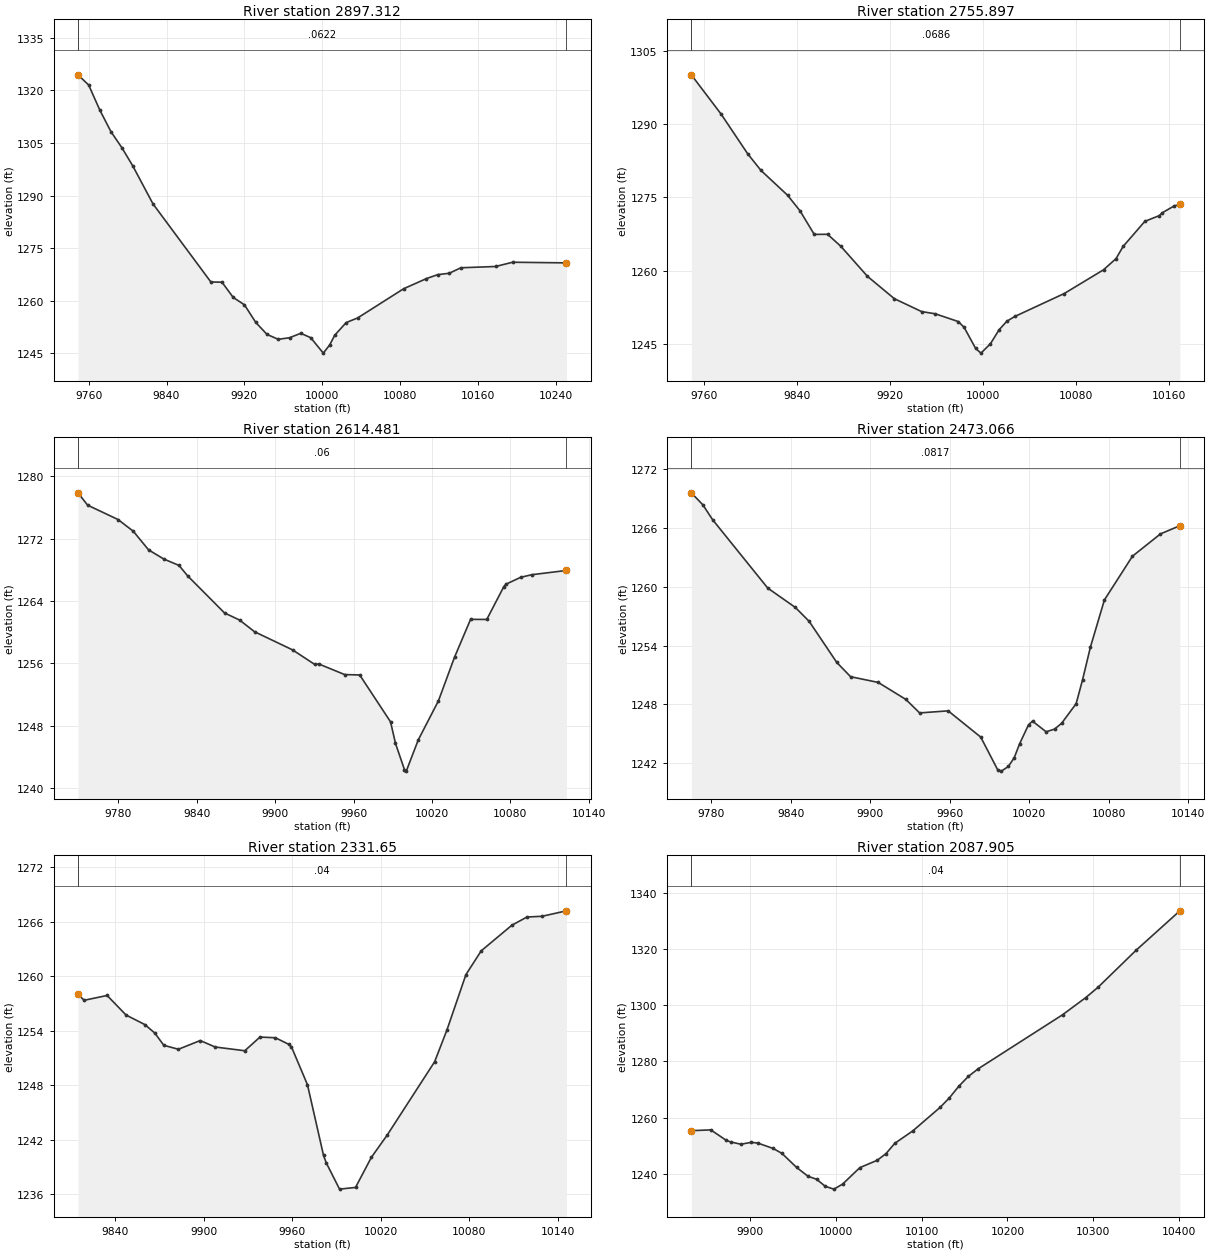
Type RM Length L Ch R = 1 ,2897.312,141.415400,141.415400,141.415400
XS GIS Cut Line= 6
749517.808243546759095.368686164749588.809834116759224.348106763
749640.430384315759313.206656416749641.452671484759314.925647092
 749708.50427098759423.002805091749774.950196211759526.284427854
#Sta/Elev= 30
9749.0051324.4589759.9991321.5549771.4141314.4219782.8291308.2759794.2441303.604
 9805.391298.4399826.1271287.6129885.5651265.344 9896.991265.2859908.5591260.924
9920.1191258.8139931.6841253.8159943.2491250.3819954.8141248.9799966.379 1249.43
9977.9441250.6979988.1891249.44110001.091245.03810007.73 1247.4110012.86 1250.15
10024.621253.76210036.39 1255.08 10083.61263.404   101071266.30310118.77 1267.44
10130.561267.83210142.451269.39610178.121269.76210195.641270.975   102511270.794
#Mann= 3 , 0 , 0
9749.005  0.0622       09749.005  0.0622       0   10251  0.0622       0
#XS Ineff= 2 , 0
       0                               0
Bank Sta=9749.005,10251
Exp/Cntr=0.3,0.1

Type RM Length L Ch R = 1 ,2755.897,141.415500,141.415500,141.415500
XS GIS Cut Line= 6
749389.309930849759172.650913472749471.338383673759319.250348503
749497.506516946759361.748296892749511.178516484 759378.77817791
749542.007341792759407.607371776749624.476297857759518.815573666
#Sta/Elev= 30
 9749.061300.066 9774.671292.0499797.5881283.9289809.047 1280.529831.9651275.446
 9842.63 1272.279854.8831267.4569866.3421267.4769877.8011265.0189900.7191258.878
9923.8011254.3239947.2881251.6829959.0321251.2329978.9271249.6369983.951 1248.44
9993.8161244.1529998.3911243.191 10006.61245.115   100141247.96510020.811249.733
 10027.6 1250.6910070.061255.366 10103.91260.21910114.691262.50910120.821265.009
10139.481270.11910151.881271.28710154.541271.88310164.71 1273.2710169.621273.616
#Mann= 3 , 0 , 0
 9749.06  0.0686       0 9749.06  0.0686       010169.62  0.0686       0
#XS Ineff= 2 , 0
       0                               0
Bank Sta=9749.06,10169.62
Exp/Cntr=0.3,0.1

Type RM Length L Ch R = 1 ,2614.481,141.415500,141.415500,141.415500
XS GIS Cut Line= 6
749271.748356849759238.670315214749323.728380221759325.136460763
749384.889998793759432.941809975749434.570021346759503.718632721
749457.671180211759531.605939233749476.234491494759550.513168124
#Sta/Elev= 30
9749.0151277.875  9756.41276.2939779.7361274.4429791.4041272.9399803.0721270.552
9814.7391269.3769826.4071268.5539832.9611267.2199861.2431262.4539872.7451261.544
9884.237 1260.049913.2761257.7189930.2261255.8529933.5411255.8959953.2211254.543
9964.7181254.4959988.3331248.4759992.0981245.719    99991242.33410000.381242.149
10009.591246.17210024.991251.168 10037.31256.768 10049.61261.631   10062 1261.62
10074.981265.80610076.681266.14610087.97 1267.0310096.541267.36510123.04 1267.91
#Mann= 3 , 0 , 0
9749.015    0.06       09749.015    0.06       010123.04    0.06       0
#XS Ineff= 2 , 0
       0                               0
Bank Sta=9749.015,10123.04
Exp/Cntr=0.3,0.1

Type RM Length L Ch R = 1 ,2473.066,141.415500,141.415500,141.415500
XS GIS Cut Line= 6
749202.553575218 759309.64348425 749257.04358682759495.664609268
749290.128094375759538.178553596749301.532052457759549.273414582
749329.407103062759564.032796189749398.675170541759588.431058362
#Sta/Elev= 30
9765.0261269.5839773.7291268.3599781.0281266.8529822.7091259.8629843.5491257.887
9853.9691256.469 9874.811252.275 9885.231250.822 9906.071250.2379926.9111248.504
9937.3311247.1279958.8641247.3379983.4531244.6589996.1711241.341    99991241.187
10004.28 1241.6610008.741242.55910012.741243.96310019.53 1245.9210022.521246.285
10032.791245.20310039.141245.47310044.461246.06410055.441248.06810060.28  1250.5
 10066.21253.82810076.781258.65310097.951263.11710119.111265.39410133.721266.227
#Mann= 3 , 0 , 0
9765.026  0.0817       09765.026  0.0817       010133.72  0.0817       0
#XS Ineff= 2 , 0
       0                               0
Bank Sta=9765.026,10133.72
Exp/Cntr=0.3,0.1

Type RM Length L Ch R = 1 , 2331.65,243.745600,243.745600,243.745600
XS GIS Cut Line= 6
749129.577271849759612.396670148749191.487791002759662.030546337
749224.521417528759664.120187297749241.829106629759659.822543383
749362.077544242759611.638124779749431.261955755 759594.80014694
#Sta/Elev= 30
9814.6181258.003 9818.781257.3379834.3851257.8689847.2021255.7189860.019 1254.66
9866.7411253.7279872.8361252.3829882.7281251.9479897.5241252.9069907.6491252.196
9927.7391251.7849938.0421253.2899948.5251253.2149957.4021252.5019959.3911252.211
9970.2581248.0389981.1241240.2729982.9551239.4569991.9911236.55210002.841236.738
10013.631240.06410024.421242.52510056.491250.57610064.791254.05110077.691260.158
10088.071262.78210108.841265.59710119.081266.503 10129.31266.585 10145.91267.185
#Mann= 3 , 0 , 0
9814.618    0.04       09814.618    0.04       0 10145.9    0.04       0
#XS Ineff= 2 , 0
       0                               0
Bank Sta=9814.618,10145.9
Exp/Cntr=0.3,0.1

Type RM Length L Ch R = 1 ,2087.905,243.745600,243.745600,243.745600
XS GIS Cut Line= 6
749106.790813506759652.544239581749186.537903249759704.936949864
749204.086036772759838.270354137749249.846248209 759950.12276113
749307.192630976 760025.91303204749399.851301879760105.791348547
#Sta/Elev= 30
9831.8191255.3539854.5041255.6349872.7161251.8759877.5371251.3679889.502 1250.53
9901.4671251.196 9909.141250.9569927.2371249.0219937.4621247.2619954.4241242.295
9967.7731239.1289977.804 1238.079987.8361235.5669997.8681234.57410007.931236.334
10028.051242.20110048.371244.83310058.531247.18810068.881250.87210089.771255.268
10121.581263.63210132.531267.05910143.471271.17810154.411274.62210165.831277.323
10264.231296.55210291.281302.66610305.561306.32610349.981319.51610400.851333.502
#Mann= 3 , 0 , 0
9831.819    0.04       09831.819    0.04       010400.85    0.04       0
#XS Ineff= 2 , 0
       0                               0
Bank Sta=9831.819,10400.85
Exp/Cntr=0.3,0.1

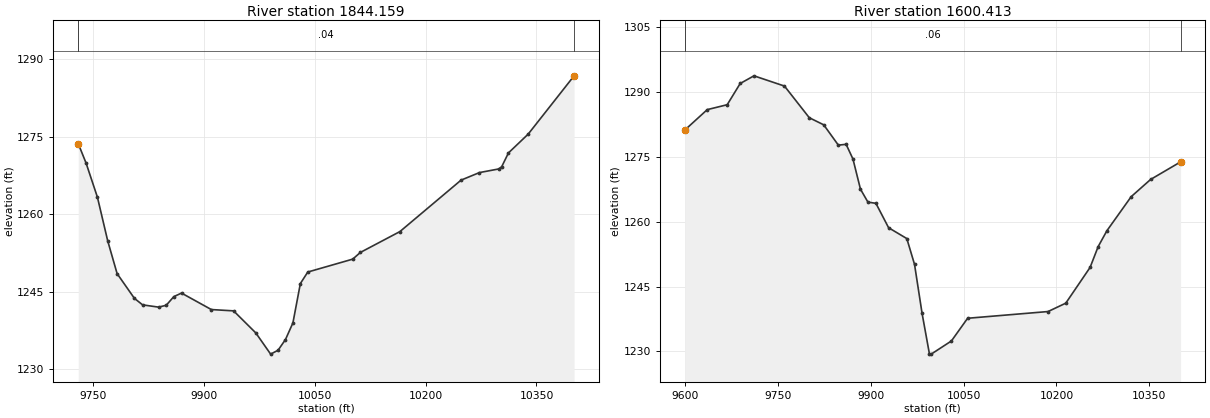
Type RM Length L Ch R = 1 ,1844.159,243.745600,243.745600,243.745600
XS GIS Cut Line= 6
748872.241616838759548.397594489748904.178992664759577.493089231
748931.780419394759625.976700959748977.273816918 759932.56170895
749041.076724769760039.685091678749132.092583984760139.168355168
#Sta/Elev= 30
 9730.481273.6899741.1521269.8959756.4571263.2949770.329 1254.869783.0641248.496
9806.4331243.708 9817.561242.4419839.1041242.0079849.4451242.3619859.7851244.046
9870.1261244.7269910.4651241.5359940.5241241.2829970.5821237.0089990.6221232.901
10000.661233.655 10010.7 1235.7310020.751238.952 10030.81246.56910040.851248.804
10101.591251.30210111.941252.59910165.431256.64310248.021266.60210272.871268.068
10299.061268.77210302.98  1269.210312.15 1271.8810338.761275.51110400.87 1286.81
#Mann= 3 , 0 , 0
 9730.48    0.04       0 9730.48    0.04       010400.87    0.04       0
#XS Ineff= 2 , 0
       0                               0
Bank Sta=9730.48,10400.87
Exp/Cntr=0.3,0.1

Type RM Length L Ch R = 1 ,1600.413,298.674700,298.674700,298.674700
XS GIS Cut Line= 6
748371.138805803 759592.06743081748561.095996125759676.940707459
748731.335668737759793.594768657748791.648899186759863.049128626
748915.006763677759967.333249345749009.409478929 760061.41225886
#Sta/Elev= 30
9599.0751281.2229635.4811285.9639667.7361287.0979688.7361292.0119711.0141293.785
9760.3331291.4139800.4661284.0859823.7891282.4459847.4241277.7459860.0171277.932
9871.0591274.5299883.2021267.5519895.2951264.5479908.179 1264.289928.6821258.626
9958.1341256.1189970.6221250.1439982.8391238.7889994.6761229.4499997.5561229.371
10030.261232.41810056.451237.67110186.511239.22710215.181241.16810254.471249.441
10267.561254.26910281.681257.93410320.931265.81710352.271269.79510400.851273.871
#Mann= 3 , 0 , 0
9599.075    0.06       09599.075    0.06       010400.85    0.06       0
#XS Ineff= 2 , 0
       0                               0
Bank Sta=9599.075,10400.85
Exp/Cntr=0.3,0.1