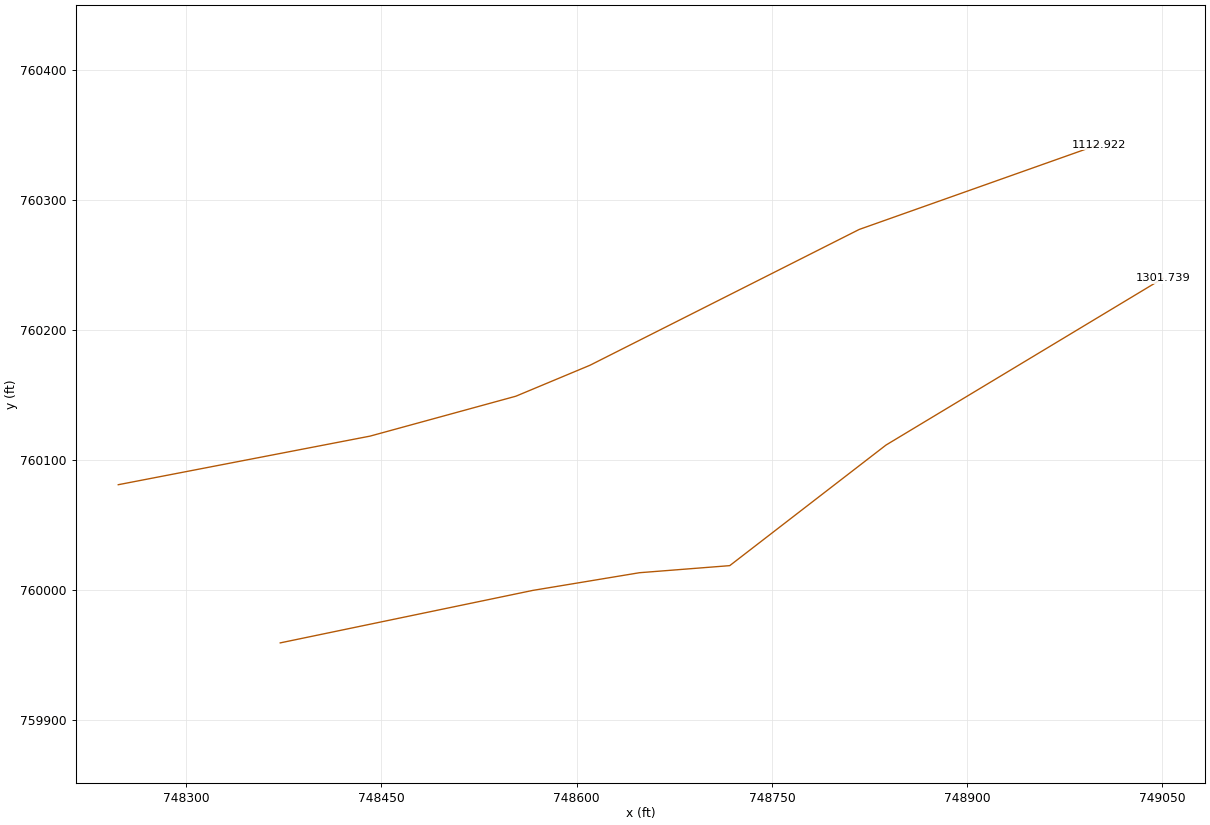
HEC-RAS study 14322_ras.prj: 14322

--- 14322_ras.g01 (geometry) --- (continued)

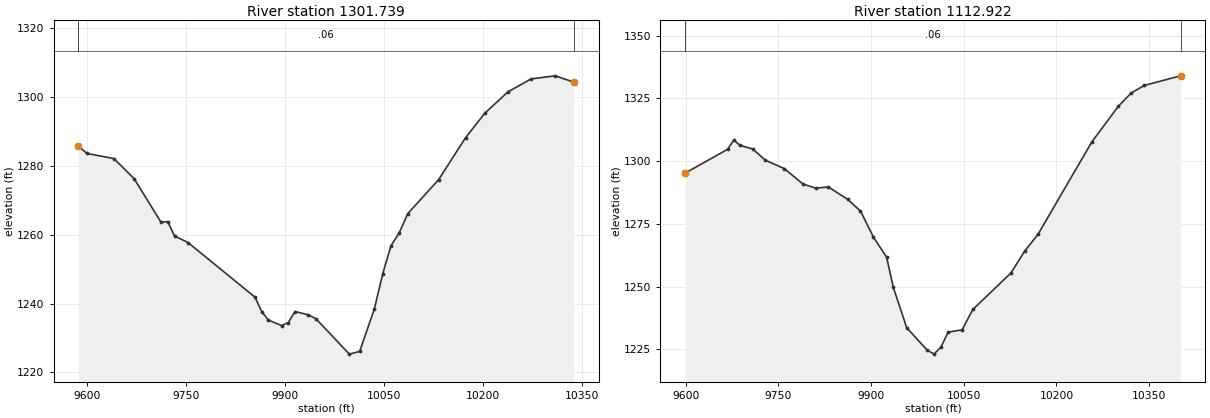
Type RM Length L Ch R = 1 ,1301.739,188.816600,188.816600,188.816600
XS GIS Cut Line= 6
748372.239989264759959.510938688748566.349789863759999.846901055
748648.245291642760013.421031699748717.594477813760018.861917207
748837.693591326760111.528614566749050.367202431760239.566809028
#Sta/Elev= 30
9586.3871285.8149599.4191283.6739640.2741282.1759670.914 1276.359711.7691263.664
9721.983 1263.849732.1961259.6759752.6231257.779 9854.231241.8799864.3661237.661
9874.4541235.2259894.5841233.6279904.6481234.5189914.7121237.7099934.7121236.779
9946.6611235.6029997.1831225.33510012.831226.12210035.08 1238.4810047.71 1248.66
10060.341256.84510072.971260.647 10085.61266.14810132.551276.06310173.281288.242
10202.581295.388 10237.61301.57410272.621305.329   10309 1306.2310337.241304.402
#Mann= 3 , 0 , 0
9586.387    0.06       09586.387    0.06       010337.24    0.06       0
#XS Ineff= 2 , 0
       0                               0
Bank Sta=9586.387,10337.24
Exp/Cntr=0.3,0.1

Type RM Length L Ch R = 1 ,1112.922,0.000000,0.000000,0.000000
XS GIS Cut Line= 6
748247.761637327760081.041465738748441.217950513760118.372290778
748553.258499305760149.040701087748610.198332937760172.818090776
748817.098593812760277.180657479 749000.93002406760342.324458074
#Sta/Elev= 30
9599.0631295.1889667.541 1304.659677.7261308.342 9687.911306.2079708.2791304.815
9728.6481300.3319759.2021297.0179789.7551290.8089810.2641289.2189830.837 1289.64
9861.8291284.7659882.7481280.0699903.6661269.7119925.0281261.6559935.8651249.654
9957.5391233.5949990.5861224.67910001.811223.05910013.151225.91610024.49  1231.8
10047.171232.74410064.611240.85610126.291255.39210148.351264.01910170.411270.922
10257.261307.63410300.211321.84510321.221327.15910342.221330.12510400.951333.944
#Mann= 3 , 0 , 0
9599.063    0.06       09599.063    0.06       010400.95    0.06       0
#XS Ineff= 2 , 0
       0                               0
Bank Sta=9599.063,10400.95
Exp/Cntr=0.3,0.1